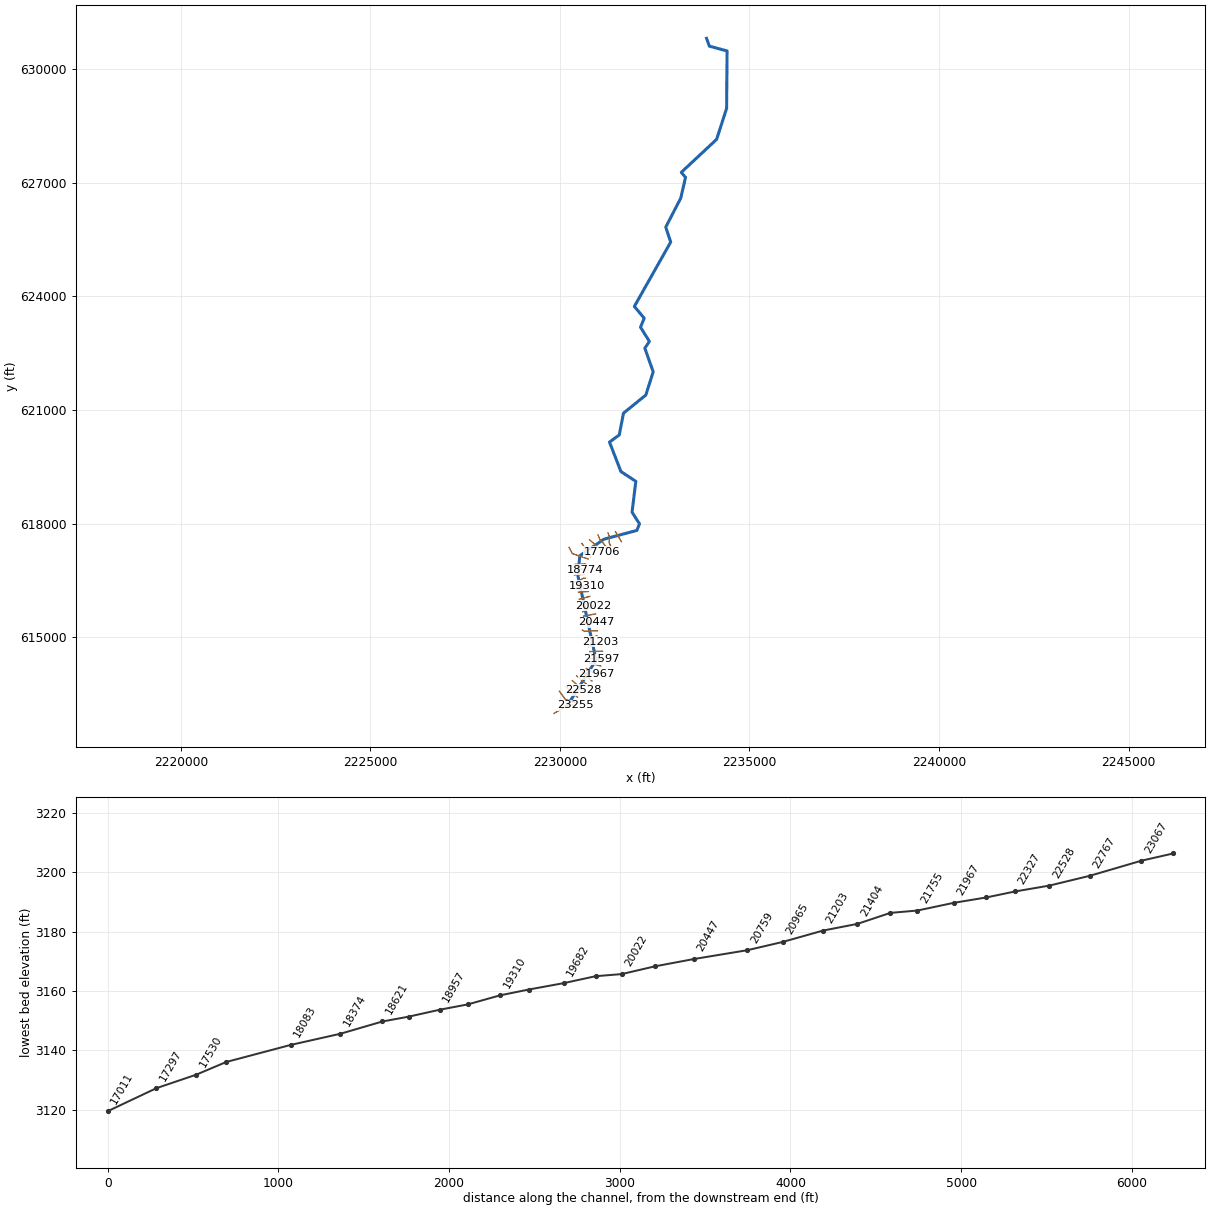
--- ROCKYRN.prj (project) ---

Proj Title=ROCKYRN
Current Plan=p01
Default Exp/Contr=0,0
English Units
Geom File=g01
Flow File=f01
Plan File=p01
BEGIN DESCRIPTION:
----------MODEL BY WOOD PLC 2022----------
AFH study
Randolph County, WV
HEC-RAS Version: RAS 6.2
Vertical Datum: NAVD88
Projection: NAD 1983 StatePlane West Virginia S FIPS 4702 (US Feet)
Terrain: 1-meter LIDAR (FEMA Region III 3DEP collected 2016-2018)
Land Use: 2019 NLCD
Hydrologic Method:
WV SIR2010-5033 regression equations
Additional Model Notes:
None
END DESCRIPTION:
DSS Export Rating Curves= 0
DSS Export Rating Curve Sorted= 0
DSS Export Volume Flow Curves= 0
DXF OffsetX= 0
DXF OffsetY= 0
DXF ScaleX= 0
DXF ScaleY= 0

--- ROCKYRN.p01 (plan) ---

Plan Title=Floodplain
Program Version=6.20
Short Identifier=Floodplain
Geom File=g01
Flow File=f01
Subcritical Flow
K Sum by GR= 0
Std Step Tol= 0.01
Critical Tol= 0.01
Num of Std Step Trials= 20
Max Error Tol= 0.3
Flow Tol Ratio= 0.001
Split Flow NTrial= 30
Split Flow Tol= 0.02
Split Flow Ratio= 0.02
Log Output Level= 0
Friction Slope Method= 1
Unsteady Friction Slope Method= 2
Unsteady Bridges Friction Slope Method= 1
Parabolic Critical Depth
Global Vel Dist= 0 , 0 , 0
Global Log Level= 0
CheckData=True
Encroach Param=-1 ,0,0, 0
Mapping Interval=1HOUR
Computation Time Step Use Courant=        0
Computation Time Step Use Time Series=    0
Computation Time Step Count To Double=0
Computation Time Step Max Doubling=0
Computation Time Step Max Halving=0
Computation Time Step Residence Courant=0
Run HTab= 0
Run UNet= 0
Run Sediment= 0
Run PostProcess= 0
Run WQNet= 0
Run RASMapper=-1
UNET Theta= 0
UNET Theta Warmup= 0
UNET ZTol= 0
UNET ZSATol= 0
UNET MxIter= 0
UNET Max Iter WO Improvement= 0
UNET MaxInSteps= 0
UNET DtIC= 0
UNET DtMin= 0
UNET MaxCRTS= 0
UNET WFStab= 0
UNET SFStab= 0
UNET WFX= 1
UNET SFX= 1
UNET Gravity=32.174
UNET 1D Methodology=Finite Difference
UNET DSS MLevel= 1
UNET Pardiso=0
UNET DZMax Abort= 0
UNET Use Existing IB Tables= 0
UNET Froude Reduction=False
UNET Froude Limit= 0
UNET Froude Power= 0
UNET D1 Cores= 0
UNET WindReference=Eulerian
UNET WindDragFormulation=Hsu (1988)
UNET D2 Coriolis=0
UNET D2 Cores= 0
UNET D2 Theta= 1
UNET D2 Theta Warmup= 1
UNET D2 Z Tol= 0.01
UNET D2 Volume Tol= 0.01
UNET D2 Max Iterations= 20
UNET D2 Equation= 0
UNET D2 RampUpFraction=0.1
UNET D2 TimeSlices= 1
UNET D2 Turbulence Formulation=Non-Conservative (original)
UNET D2 Eddy Viscosity=0.3
UNET D2 Transverse Eddy Viscosity=0.1
UNET D2 Smagorinsky Mixing=0
UNET D2 BCVolumeCheck=0
UNET D2 Cores=0
UNET D2 SolverType=PARDISO (Direct)
UNET D2 Minimum Iterations= 2147483647
UNET D2 Maximum Iterations= 2147483647
UNET D2 Restart Number= 10
UNET D2 Relaxation Coeff=1.3
UNET D2 SOR Precondition Iterations= 10
UNET D2 ILUT Maximum Fill= 8
UNET D2 ILUT Tolerance=1E-08
UNET D1D2 MaxIter= 0
UNET D1D2 ZTol=0.01
UNET D1D2 QTol=0.1
UNET D1D2 MinQTol=1
Write IC File= 0
Write IC File at Fixed DateTime=0
Write IC File at Sim End=0
Echo Input=False
Echo Parameters=False
Echo Output=False
Write Detailed= 0
HDF Write Warmup=0
HDF Write Time Slices=0
HDF Flush=0
HDF Compression= 1
HDF Chunk Size= 1
HDF Spatial Parts= 1
HDF Use Max Rows=0
HDF Fixed Rows= 1
Calibration Method= 0
Calibration Iterations= 20
Calibration Max Change=0.05
Calibration Tolerance=0.2
Calibration Maximum=1.5
Calibration Minimum=0.5
Calibration Optimization Method= 1
WQ AD Non Conservative
WQ ULTIMATE=-1
WQ Max Comp Step=1HOUR
WQ Output Interval=15MIN
WQ Output Selected Increments= 0
WQ Output face flow=0
WQ Output face velocity=0
WQ Output face area=0
WQ Output face dispersion=0
WQ Output cell volume=0
WQ Output cell surface area=0
WQ Output cell continuity=0
WQ Output cumulative cell continuity=0
WQ Output face conc=0
WQ Output face dconc_dx=0
WQ Output face courant=0
WQ Output face peclet=0
WQ Output face adv mass=0
WQ Output face disp mass=0
WQ Output cell mass=0
WQ Output cell source sink temp=0
WQ Output nsm pathways=0
WQ Output nsm derived pathways=0
WQ Create Restart=0
WQ Fixed Restart=0
WQ System Summary=0
WQ Write To DSS=0
Sorting and Armoring Iterations= 10
XS Update Threshold= 0.02
Bed Roughness Predictor= 0
Hydraulics Update Threshold= 0.02
Energy Slope Method= 1
Volume Change Method= 1
Sediment Retention Method= 0
Sediment TS Multiplier= 1
Warm Up Method= 0
XS Weighting Method= 0
Number of US Weighted Cross Sections= 1
Number of DS Weighted Cross Sections= 1
Upstream XS Weight=0
Main XS Weight=1
Downstream XS Weight=0
Number of DS XS's Weighted with US Boundary= 1
Upstream Boundary Weight= 1
Weight of XSs Associated with US Boundary= 0
Number of US XS's Weighted with DS Boundary= 1
Downstream Boundary Weight= 0.5
Weight of XSs Associated with DS Boundary= 0.5
Percentile Method= 0
Sediment Output Level= 3
Mass or Volume Output= 0
Output Increment Type= 1
Profile and TS Output Increment= 1
Transport Output Increment 1
XS Output Flag= 0
XS Output Increment= 10
Read HDF5 Sediment Hotstart= 0
Sediment Hotstart Type= 0
Write Gradation File= 0
Read Gradation Hotstart= 0
Write HDF5 File= 1
Write Binary Output= 1
Write DSS Sediment File= 0
DSS Sediment Output Type= 1
SV Curve= 0
Specific Gage Flag= 0
Subcell Erosion Methods= 0
Subcell Deposition Methods= 0
Advection Scheme= 1
Matrix Solver= 0
Implicit Weighting Factor= 1
Maximum Outer Loop Convergence Iterations= 5
Convergence Maximum Absolute= 0.001
Convergence RMSE= 0.0001
Grain Fractions Max Abs Error= 0.001
Max Subgrid Regions= 1
Max Subgrid Length Scale= 3.402823E+38
Initial Layer Thickness= 3.402823E+38
Min Layer Thickness= 3.402823E+38
Max Layer Thickness= 3.402823E+38
Number of Layers= 5

--- ROCKYRN.f01 (steady flow) ---

Flow Title=Flow
Program Version=4.00
Number of Profiles=1
Profile Names=P100yr
River Rch & RM=ROCKYRN,Main,23255
     491
River Rch & RM=ROCKYRN,Main,18374
     579
River Rch & RM=ROCKYRN,Main,13996
     659
River Rch & RM=ROCKYRN,Main,9133
     733
River Rch & RM=ROCKYRN,Main,4157
     832
Boundary for River Rch & Prof#=ROCKYRN,Main      ,1
Up Type=0
Dn Type=3
Dn Slope=0.026747

--- ROCKYRN.g01 (geometry) ---

Geom Title=Geometry
Program Version=6.20

River Reach=ROCKYRN         ,Main
Reach XY= 30
2230189.92139169613191.724430592      2230954.01      614405.741
2230475.23724646 616625.929190622230524.62167526 617156.29920008
      2231161.71      617592.877     2232030.283      617824.404
2232098.84567353617998.466885279     2231903.246      618304.351
2232002.36095574619117.9900487472231608.73565532619378.221451065
2231307.86423128620154.6201916062231565.12936351620341.331006637
     2231677.337      620917.305     2232266.249      621394.486
2232460.80644849622007.5797437322232239.75731074622631.642243341
2232360.66723517622808.008977793     2232126.138      623182.985
     2232223.682      623420.857     2231963.636      623731.883
     2232922.262      625429.537     2232792.136      625824.627
     2233188.059      626589.1982233313.63315676627134.967562147
     2233201.311      627268.443     2234132.812      628137.517
     2234397.231      628956.828     2234408.866      630469.102
      2233941.72       630598.01      2233868.12       630802.93

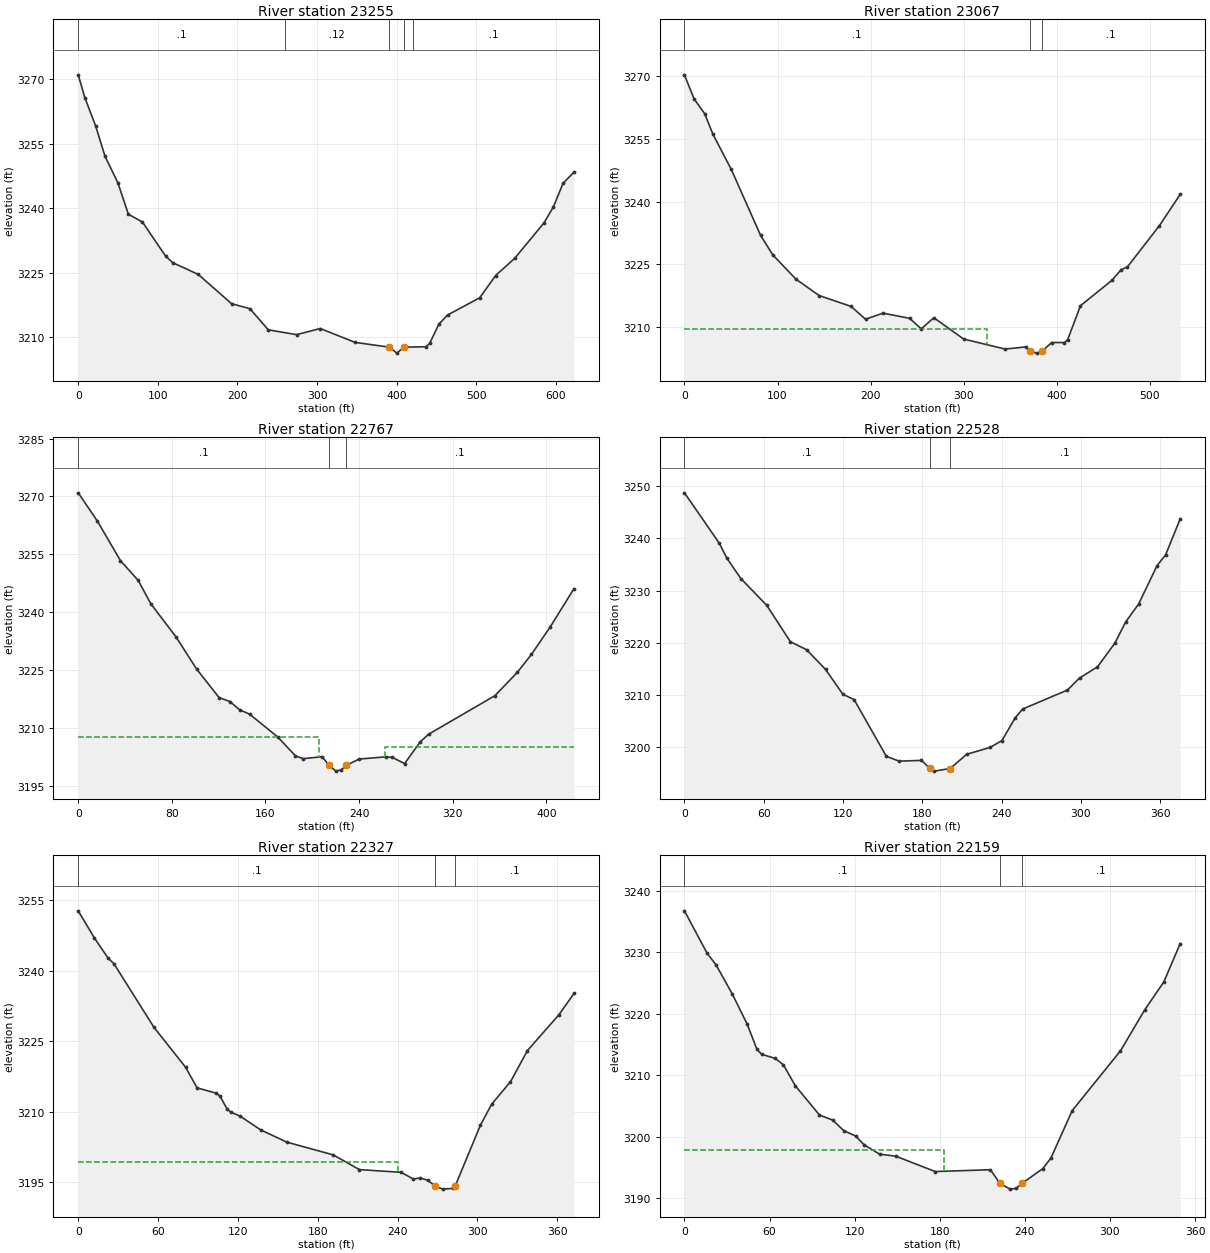
Type RM Length L Ch R = 1 ,23255   ,189.6,187.8,171.5
XS GIS Cut Line= 3
2229844.86063058612998.5001721182230244.68876204 613226.65068781
2230405.82476982613208.579359834
#Sta/Elev= 30
       0 3270.97     8.4 3265.63      22 3259.04    33.7 3252.04    49.9 3245.85
      63 3238.58    80.6 3236.79   109.7 3228.87   118.7 3227.33   150.7 3224.61
   192.6  3217.8   215.7 3216.63   238.7 3211.73   274.2 3210.61     304 3212.04
   347.5 3208.82   390.7 3207.71   400.2 3206.32   408.9 3207.71   436.7  3207.8
   441.3 3208.56     453 3213.08   463.9 3215.18   504.1 3219.17   524.2 3224.35
   548.1 3228.34   584.6 3236.51   596.7 3240.28   608.8 3245.77   622.5 3248.36
#Mann= 5 ,-1,0
       0      .1       0     260     .12       0   390.7    .045       0
   408.9     .12       0     420      .1       0
Bank Sta=390.7,408.9
XS Rating Curve= 0 ,0
Exp/Cntr(USF)=0,0
Exp/Cntr=0.3,0.1

Type RM Length L Ch R = 1 ,23067   ,301,300.6,293.3
XS GIS Cut Line= 4
2229985.94019823613581.3576208182230145.59563146613366.252995207
2230286.13065353613323.2320700852230397.98505885613286.903288871
#Sta/Elev= 30
       0 3270.23    10.3 3264.51    21.7 3260.98    30.6 3256.06    50.3 3247.67
    81.8 3231.93    94.9 3227.29   119.8 3221.49   144.7 3217.59     179    3215
   194.5 3211.95   213.3 3213.39   241.9 3212.16   254.3 3209.65   267.9  3212.3
   299.9 3207.22   344.5 3204.83   366.8 3205.34     371 3204.37   378.7 3203.86
  384.353204.373   394.5 3206.39   408.2 3206.38   411.7 3207.11   425.4 3215.17
   459.4 3221.26   468.9 3223.73   475.9 3224.45   510.2 3234.27   532.5 3241.71
#Mann= 3 ,-1,0
       0      .1       0     371    .045       0  384.35      .1       0
#XS Ineff= 2 , 0
          324.56 3209.51
Permanent Ineff=
       F       F
Bank Sta=371,384.35
XS Rating Curve= 0 ,0
Exp/Cntr(USF)=0,0
Exp/Cntr=0.3,0.1

Type RM Length L Ch R = 1 ,22767   ,238.5,238.7,238.7
XS GIS Cut Line= 2
2230150.37573425613710.4203961852230462.99445681613424.570249262
#Sta/Elev= 30
       0 3270.93    16.3 3263.65    36.1 3253.36    51.2 3248.26    62.1 3242.16
    83.7 3233.53   101.2 3225.24   120.4 3217.86   129.6 3216.84   137.9  3214.7
   146.5 3213.56   170.5 3207.64   185.6 3202.77   192.1 3202.02   208.4 3202.54
   214.5 3200.27   220.2  3198.8   224.7 3199.12  229.173200.304     240 3201.93
   262.6  3202.5   268.3 3202.38   278.9 3200.76   292.3  3206.4   299.4 3208.36
   356.1 3218.36   375.3 3224.42   387.3 3229.06   403.5 3236.25   423.6 3246.09
#Mann= 3 ,-1,0
       0      .1       0   214.5    .045       0  229.17      .1       0
#XS Ineff= 2 , 0
          205.87 3207.57  262.04         3205.08
Permanent Ineff=
       F       F
Bank Sta=214.5,229.17
XS Rating Curve= 0 ,0
Exp/Cntr(USF)=0,0
Exp/Cntr=0.3,0.1

Type RM Length L Ch R = 1 ,22528   ,199.5,200.6,199.8
XS GIS Cut Line= 2
2230328.19555809 613862.427664952230609.26560222613613.862319799
#Sta/Elev= 30
       0  3248.7    26.4 3239.05    32.1  3236.2    42.7  3232.3    62.3 3227.18
    80.2 3220.22    92.5 3218.68   106.8 3214.92   119.9 3210.17   128.4 3209.15
   152.8 3198.31   162.4 3197.38   179.4 3197.52  185.763195.994   189.1 3195.47
   201.1 3195.97   213.6 3198.69   231.3    3200   240.3 3201.32   250.2 3205.61
   255.9 3207.34   289.9 3210.98     299 3213.27   312.6 3215.42   325.7 3219.92
     334 3224.03   343.8 3227.46   357.7 3234.78   364.2 3236.86   375.2 3243.71
#Mann= 3 ,-1,0
       0      .1       0  185.76    .045       0   201.1      .1       0
Bank Sta=185.76,201.1
XS Rating Curve= 0 ,0
Exp/Cntr(USF)=0,0
Exp/Cntr=0.3,0.1

Type RM Length L Ch R = 1 ,22327   ,168.9,168.5,168
XS GIS Cut Line= 2
2230442.91802508613985.7543169662230728.76817201613746.749177399
#Sta/Elev= 30
       0  3252.7    12.1 3246.96    22.5 3242.63    26.9 3241.44      57 3227.89
    80.8 3219.39    89.3 3215.05   103.5 3213.93   106.4 3213.35     112 3210.51
   114.9 3209.84   121.6 3209.04   137.2  3206.1   156.8  3203.5   191.6 3200.79
   211.4 3197.65   242.7 3197.08   251.9 3195.65   257.1 3195.88   262.6 3195.38
   268.2 3194.18   273.9  3193.5   281.5 3193.66  283.453194.227   302.3  3207.1
   310.8 3211.59   324.9 3216.34   337.6 3222.95   361.4 3230.63   372.6 3235.12
#Mann= 3 ,-1,0
       0      .1       0   268.2    .045       0  283.45      .1       0
#XS Ineff= 2 , 0
          240.31 3199.19
Permanent Ineff=
       F       F
Bank Sta=268.2,283.45
XS Rating Curve= 0 ,0
Exp/Cntr(USF)=0,0
Exp/Cntr=0.3,0.1

Type RM Length L Ch R = 1 ,22159   ,188.2,191.4,191.7
XS GIS Cut Line= 2
2230593.01325273614096.6527017262230844.44665956613853.823479925
#Sta/Elev= 30
       0 3236.78      16 3229.86    22.3 3227.98    33.8 3223.21    44.3 3218.29
    51.1 3214.24    54.4 3213.43    64.1 3212.75    69.8 3211.71    78.2 3208.29
    95.2 3203.54   104.5 3202.72   112.2 3201.02   120.7 3200.12   126.7 3198.69
   137.6 3197.17     149 3196.84   176.8 3194.34   215.7 3194.64   222.5  3192.4
   229.6 3191.48   233.8  3191.6     238 3192.41   252.6 3194.82   258.3 3196.51
   273.4 3204.27   307.4 3213.99   324.4 3220.63     338 3225.22   349.5 3231.45
#Mann= 3 ,-1,0
       0      .1       0   222.5    .045       0     238      .1       0
#XS Ineff= 2 , 0
          183.08 3197.78
Permanent Ineff=
       F       F
Bank Sta=222.5,238
XS Rating Curve= 0 ,0
Exp/Cntr(USF)=0,0
Exp/Cntr=0.3,0.1

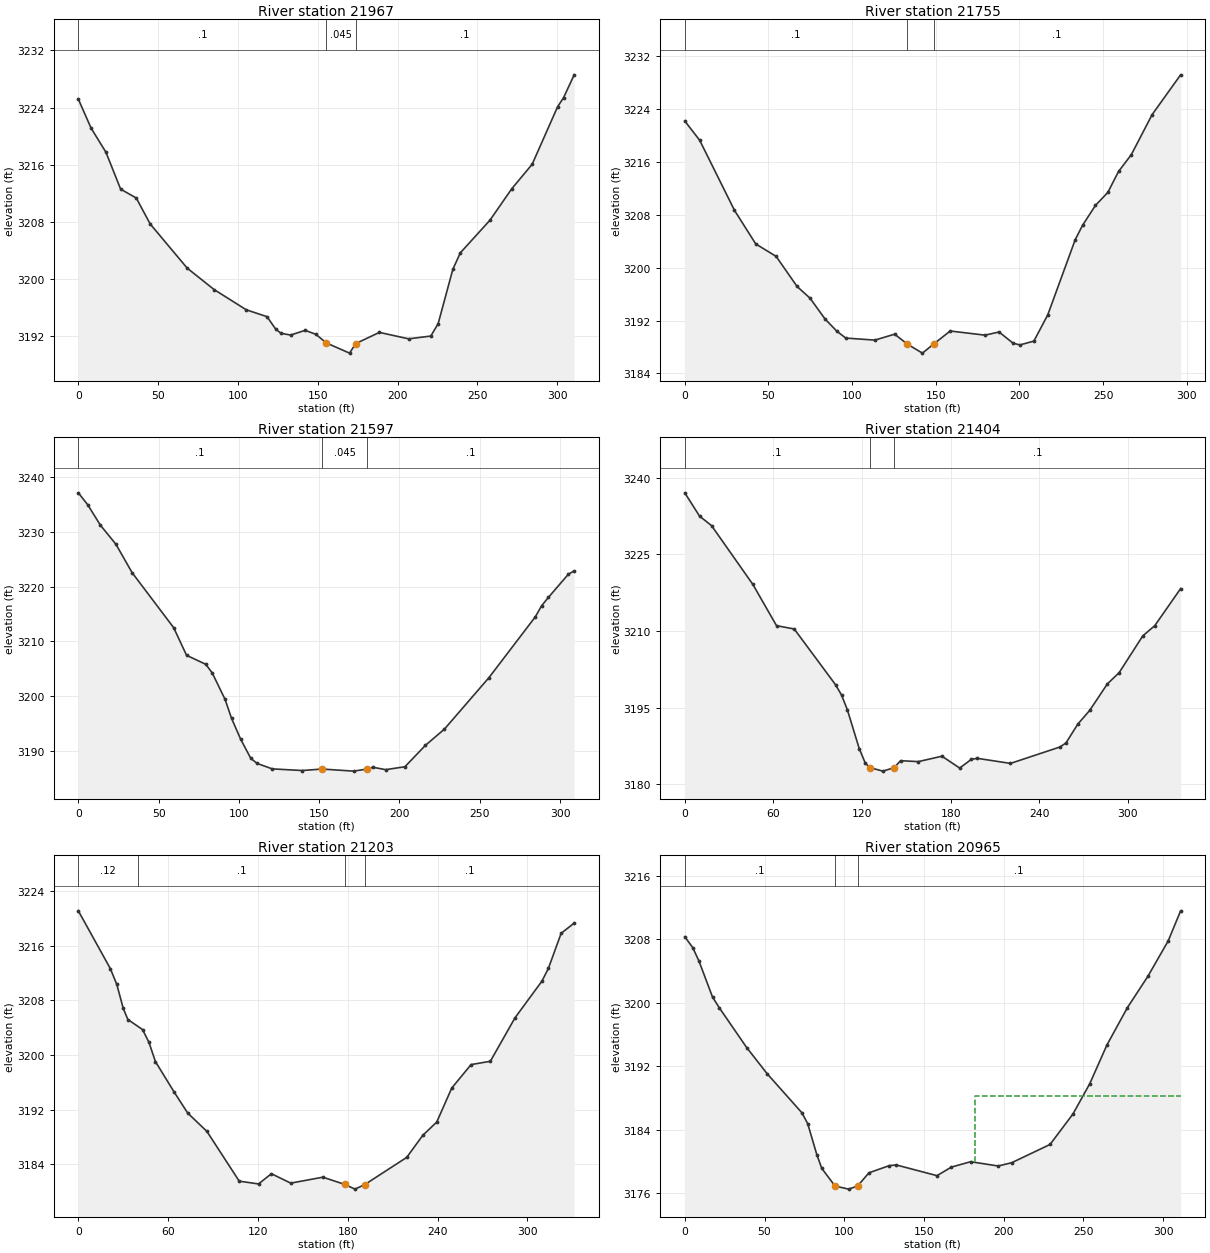
Type RM Length L Ch R = 1 ,21967   ,210.6,212.7,214.7
XS GIS Cut Line= 2
2230697.21949358614179.8264902952230965.86127046614023.995139297
#Sta/Elev= 30
       0 3225.19       8 3221.13    17.3 3217.76    26.5  3212.6    36.3 3211.36
      45 3207.73    68.2 3201.55      85 3198.56   105.2 3195.72   118.2 3194.76
   123.6 3193.03     127 3192.43     133 3192.19   142.1 3192.85   148.8 3192.29
   155.33191.093   169.9 3189.66   173.8    3191   188.6 3192.56   206.9 3191.66
   220.8 3192.05   225.4 3193.78   234.6 3201.38   239.3 3203.69   257.8 3208.24
   271.6 3212.68   284.3 3216.08   300.2 3224.11     304 3225.41   310.6 3228.59
#Mann= 3 ,-1,0
       0      .1       0   155.3    .045       0   173.8      .1       0
Bank Sta=155.3,173.8
XS Rating Curve= 0 ,0
Exp/Cntr(USF)=0,0
Exp/Cntr=0.3,0.1

Type RM Length L Ch R = 1 ,21755   ,155,158,162.5
XS GIS Cut Line= 2
2230791.62148016614329.0252063692231076.51560653614247.763458916
#Sta/Elev= 30
       0 3222.21     8.9 3219.29    29.7 3208.68    42.4  3203.6    54.6 3201.71
    67.1 3197.16    74.8  3195.4    83.8 3192.24    90.9 3190.38    96.2 3189.35
   113.6 3189.04   125.4 3189.94   132.93188.448     142 3187.07  148.64 3188.43
   158.6 3190.42   179.4 3189.79   187.8 3190.27   196.1 3188.59   200.2 3188.31
   208.6 3188.89   216.9 3192.86   233.3 3204.24   237.7 3206.42   245.4 3209.43
   252.8  3211.4   259.2 3214.57   266.8  3217.1   279.3 3223.19   296.3  3229.2
#Mann= 3 ,-1,0
       0      .1       0   132.9    .045       0  148.64      .1       0
Bank Sta=132.9,148.64
XS Rating Curve= 0 ,0
Exp/Cntr(USF)=0,0
Exp/Cntr=0.3,0.1

Type RM Length L Ch R = 1 ,21597   ,191.9,192.8,194.8
XS GIS Cut Line= 3
2230792.82154941 614442.732143822231031.82668898614444.644184936
2231099.70414862614428.391835446
#Sta/Elev= 30
       0 3237.17     5.8 3235.01    13.7 3231.27    23.4 3227.77    33.5 3222.57
    59.4  3212.5    67.4 3207.46    79.4 3205.81    83.4 3204.23    91.4 3199.39
    95.4 3195.95     101 3192.18   107.4 3188.61   111.4 3187.68   120.8 3186.69
   139.4 3186.39   151.7 3186.66   171.4 3186.28  179.88 3186.66   183.4 3186.99
   191.4 3186.55   203.4 3187.08   216.1 3190.98     228 3193.96   255.8  3203.4
   284.6 3214.49   288.6 3216.55   292.8 3218.06   305.2 3222.29   308.8 3222.89
#Mann= 3 ,-1,0
       0      .1       0   151.7    .045       0  179.88      .1       0
Bank Sta=151.7,179.88
XS Rating Curve= 0 ,0
Exp/Cntr(USF)=0,0
Exp/Cntr=0.3,0.1

Type RM Length L Ch R = 1 ,21404   ,197.5,201,201.8
XS GIS Cut Line= 2
 2230786.1294055614629.1561526832231121.69262146614637.760337707
#Sta/Elev= 30
       0 3237.01      10 3232.45    18.1  3230.6    46.1 3219.09    62.1 3211.03
    74.1 3210.38   102.1 3199.46   106.1 3197.47   110.1 3194.55   118.1 3186.99
   122.1 3184.22  125.163183.274   134.1 3182.58   141.7 3183.25   146.1 3184.62
   158.1 3184.44   174.1  3185.5   186.1 3183.18   194.1  3184.9   198.1 3185.08
   220.5 3184.09   254.1 3187.31   258.1  3188.1   266.1 3191.78   274.1 3194.44
   286.1 3199.64   294.1 3201.85   310.1 3209.04   318.2 3211.03   335.7 3218.28
#Mann= 3 ,-1,0
       0      .1       0  125.16    .045       0   141.7      .1       0
Bank Sta=125.16,141.7
XS Rating Curve= 0 ,0
Exp/Cntr(USF)=0,0
Exp/Cntr=0.3,0.1

Type RM Length L Ch R = 1 ,21203   ,235.2,237.6,234.6
XS GIS Cut Line= 2
2230760.31685043614762.0430102822231068.15547019614884.413641741
#Sta/Elev= 30
       0 3221.14    21.4 3212.66    25.7 3210.35      30 3206.84    33.1  3205.2
    42.9 3203.73    47.2 3201.85    51.5 3199.04    63.9 3194.61    73.1 3191.48
    85.9  3188.8   107.5  3181.5   120.4 3181.09     129 3182.59   141.9 3181.21
   163.4 3182.08   177.9 3181.03   184.9 3180.33  191.423181.003   219.4 3184.98
   230.2 3188.23   239.5 3190.17   249.5 3195.15   262.4 3198.59   275.3 3199.08
   291.8 3205.46   309.8 3210.84   314.1 3212.71   322.6 3217.84   331.3 3219.34
#Mann= 4 ,-1,0
       0     .12       0      40      .1       0   177.9    .045       0
  191.42      .1       0
Bank Sta=177.9,191.42
XS Rating Curve= 0 ,0
Exp/Cntr(USF)=0,0
Exp/Cntr=0.3,0.1

Type RM Length L Ch R = 1 ,20965   ,207.6,206.4,205.1
XS GIS Cut Line= 2
2230683.83520577614935.0827313292230975.42147604615043.113054414
#Sta/Elev= 30
       0 3208.35       5 3206.97     8.9 3205.27    17.4 3200.73    21.7 3199.36
    38.8 3194.36    51.7 3191.04    73.5 3186.11    77.1 3184.74    82.8 3180.84
    85.9 3179.11    94.2 3176.88   102.7 3176.48  108.333176.864   115.5 3178.54
   128.3 3179.45   132.7 3179.53   158.2 3178.18   167.2 3179.26   179.3 3179.94
   196.6  3179.4   205.1 3179.82   229.1 3182.12   243.5 3185.98     254 3189.79
   264.8 3194.69   277.6 3199.39   290.4 3203.33   303.2 3207.82     311 3211.62
#Mann= 3 ,-1,0
       0      .1       0    94.2    .045       0  108.33      .1       0
#XS Ineff= 2 , 0
                           182.2         3188.24
Permanent Ineff=
       F       F
Bank Sta=94.2,108.33
XS Rating Curve= 0 ,0
Exp/Cntr(USF)=0,0
Exp/Cntr=0.3,0.1

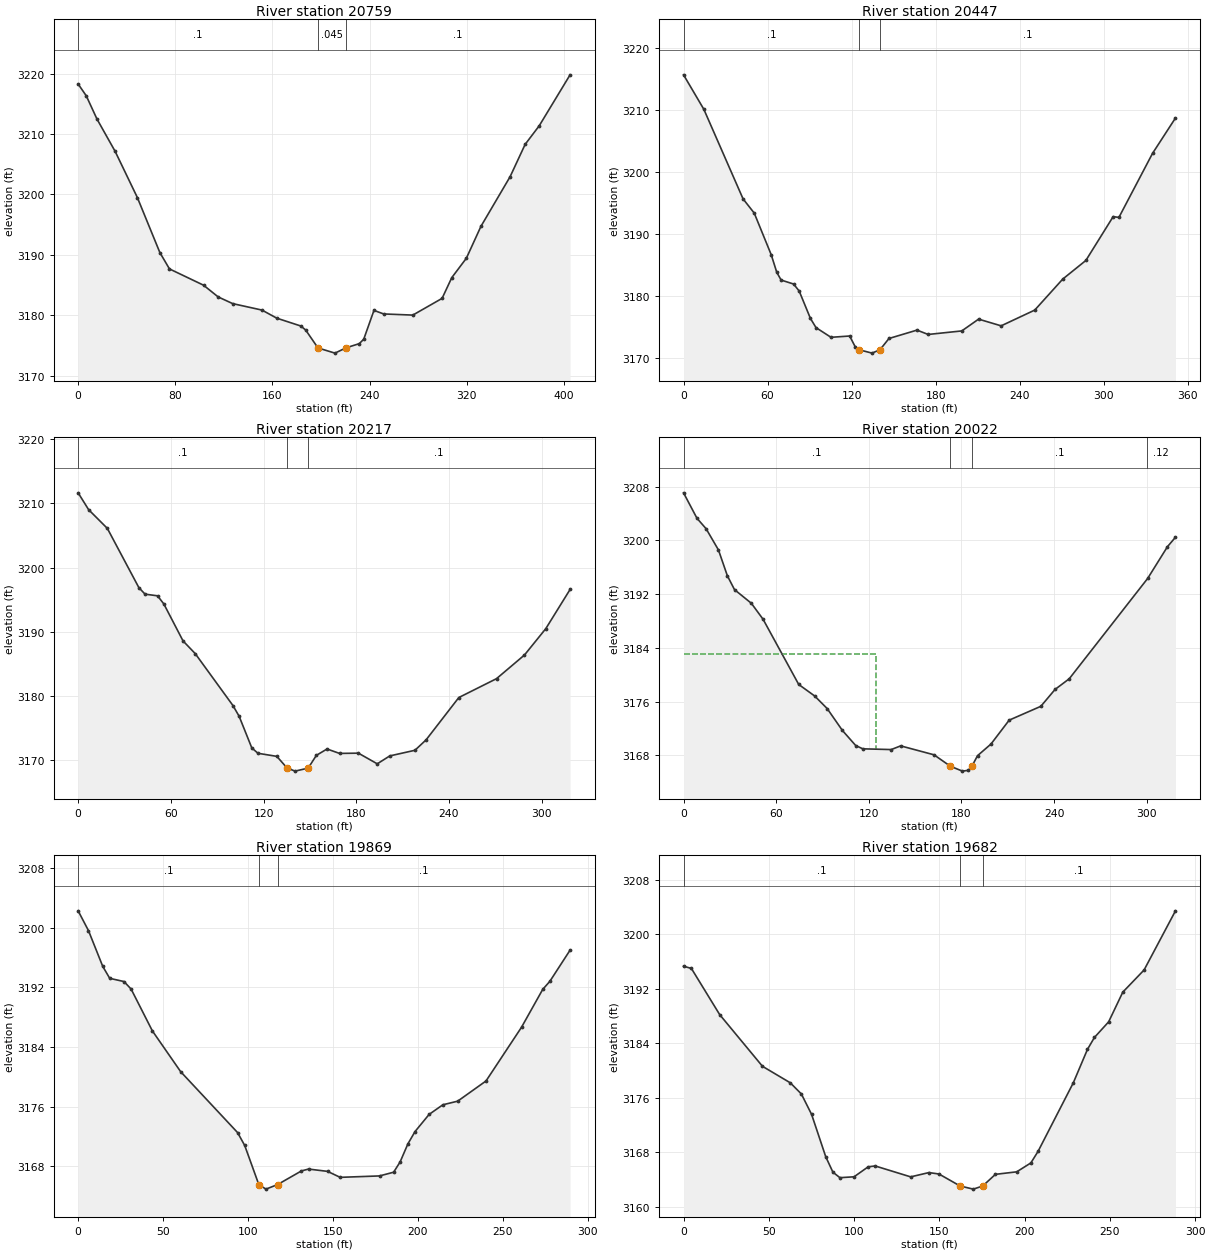
Type RM Length L Ch R = 1 ,20759   ,308.9,311.5,309.1
XS GIS Cut Line= 4
2230593.57140841  615195.69359952230652.27812699615162.796075852
2230885.56226385 615177.724781192230989.57629255 615176.19380424
#Sta/Elev= 30
       0 3218.29     6.7 3216.33    15.5 3212.49    30.5 3207.12    48.8 3199.47
    67.3 3190.37    75.2 3187.66   103.3 3184.96   115.3 3183.02   127.3 3181.91
   151.4 3180.84   163.6  3179.5   183.4  3178.2   187.4 3177.53197.51263174.568
   211.5 3173.71 220.6193174.591   231.5 3175.28   235.2 3176.02   243.6 3180.79
   251.6  3180.2   275.6 3180.01   299.7 3182.78   307.7 3186.22   319.7 3189.43
   331.7 3194.71   355.7 3202.93   368.1 3208.29   379.7 3211.37   405.1 3219.81
#Mann= 3 ,-1,0
       0      .1       0197.5126    .045       0 220.619      .1       0
Bank Sta=197.5126,220.619
XS Rating Curve= 0 ,0
Exp/Cntr(USF)=0,0
Exp/Cntr=0.3,0.1

Type RM Length L Ch R = 1 ,20447   ,227.3,229.9,229.3
XS GIS Cut Line= 2
2230621.69386948615378.6762703672230972.55341437615395.884640416
#Sta/Elev= 30
       0 3215.62    14.5 3210.06    42.5 3195.62    50.5 3193.32    62.6 3186.62
    66.6 3183.76    69.7 3182.53    78.6 3181.89    82.6 3180.75    90.6 3176.35
    94.6 3174.86   105.3  3173.3   118.6 3173.51   122.6 3171.77  125.283171.299
   134.6 3170.75  140.313171.304   146.7 3173.11   166.7 3174.46   174.7 3173.76
   198.7 3174.33   210.7 3176.23   226.8 3175.15   250.8 3177.69   270.8 3182.69
   287.3 3185.69   306.8 3192.76   310.9 3192.63   334.9 3202.95   351.3 3208.66
#Mann= 3 ,-1,0
       0      .1       0  125.28    .045       0  140.31      .1       0
Bank Sta=125.28,140.31
XS Rating Curve= 0 ,0
Exp/Cntr(USF)=0,0
Exp/Cntr=0.3,0.1

Type RM Length L Ch R = 1 ,20217   ,191.3,195,196.3
XS GIS Cut Line= 2
2230625.51795171 615565.100279232230939.09269483615620.549471609
#Sta/Elev= 30
       0 3211.64     6.8 3209.01    18.9  3206.1    39.3 3196.87    43.3 3195.85
    51.4 3195.59    55.5 3194.31    67.9 3188.56    75.8 3186.58   100.2 3178.49
   104.2 3176.82   112.4 3171.89   116.4 3171.05   128.6 3170.57  135.183168.769
   140.4 3168.27   148.9 3168.74   154.2 3170.73   161.1 3171.72   169.2 3171.03
   181.4 3171.07   193.6 3169.41   201.7 3170.64     218 3171.52   225.2 3173.14
   246.4 3179.74   270.8 3182.68   288.9 3186.37   302.7 3190.48   318.4 3196.58
#Mann= 3 ,-1,0
       0      .1       0  135.18    .045       0   148.9      .1       0
Bank Sta=135.18,148.9
XS Rating Curve= 0 ,0
Exp/Cntr(USF)=0,0
Exp/Cntr=0.3,0.1

Type RM Length L Ch R = 1 ,20022   ,154.4,153.1,153
XS GIS Cut Line= 2
2230603.52947887615677.9107051052230879.81942021615836.610117778
#Sta/Elev= 30
       0 3207.09     8.7  3203.3    14.6 3201.75    22.6 3198.59    28.4 3194.73
      33 3192.68    43.9 3190.65    51.5 3188.27    74.6 3178.56    84.9 3176.85
      93 3174.98   102.9 3171.71   111.5 3169.47   116.1 3168.98   134.5 3168.87
   140.6 3169.42   162.2 3168.09   172.8 3166.39   180.6 3165.66   184.5 3165.78
  186.833166.422   190.4 3167.96   199.1 3169.69   210.9 3173.25   231.4 3175.31
   240.6 3177.82   249.8 3179.41   300.6 3194.35   313.4 3199.07   318.6 3200.48
#Mann= 4 ,-1,0
       0      .1       0   172.8    .045       0  186.83      .1       0
     300     .12       0
#XS Ineff= 2 , 0
          124.33  3183.1
Permanent Ineff=
       F       F
Bank Sta=172.8,186.83
XS Rating Curve= 0 ,0
Exp/Cntr(USF)=0,0
Exp/Cntr=0.3,0.1

Type RM Length L Ch R = 1 ,19869   ,187.4,187.3,188.2
XS GIS Cut Line= 2
2230542.34416314615838.5221588952230819.59012504615922.651968023
#Sta/Elev= 30
       0 3202.25     6.1 3199.59    14.5  3194.8    18.6  3193.2      27 3192.77
    31.2 3191.76    43.7 3186.16    60.4 3180.68    93.9 3172.52    98.1 3170.79
   106.4 3165.55   110.6 3164.94  117.493165.556   131.5 3167.38   135.7 3167.63
   146.9 3167.32   154.3 3166.52   177.5 3166.71   185.8 3167.21   189.6 3168.58
   194.2 3171.01   198.4 3172.66   206.7 3174.96   214.8 3176.25   223.5 3176.73
   240.2 3179.44   261.1 3186.64   273.6 3191.72   277.8  3192.8   289.7 3196.98
#Mann= 3 ,-1,0
       0      .1       0   106.4    .045       0  117.49      .1       0
Bank Sta=106.4,117.49
XS Rating Curve= 0 ,0
Exp/Cntr(USF)=0,0
Exp/Cntr=0.3,0.1

Type RM Length L Ch R = 1 ,19682   ,204.3,204.6,200.3
XS GIS Cut Line= 2
2230511.75150528616008.6938182672230789.95348774616085.175462929
#Sta/Elev= 30
       0 3195.33     4.6    3195    21.2 3188.22    46.3 3180.63    62.6 3178.21
    69.1 3176.57    75.1 3173.57    83.4 3167.35    87.6 3165.09    91.7 3164.28
     100 3164.41   108.3 3165.88   112.4    3166   133.2  3164.4   143.9 3165.03
   149.8 3164.82   162.2 3163.06   169.9  3162.6  175.393163.049   182.9 3164.77
   195.4 3165.14   203.7 3166.45   207.9 3168.14   228.6 3178.22   236.9 3183.13
     241 3184.88   249.3 3187.16   257.6 3191.52   270.1 3194.78   288.5 3203.46
#Mann= 3 ,-1,0
       0      .1       0   162.2    .045       0  175.39      .1       0
Bank Sta=162.2,175.39
XS Rating Curve= 0 ,0
Exp/Cntr(USF)=0,0
Exp/Cntr=0.3,0.1

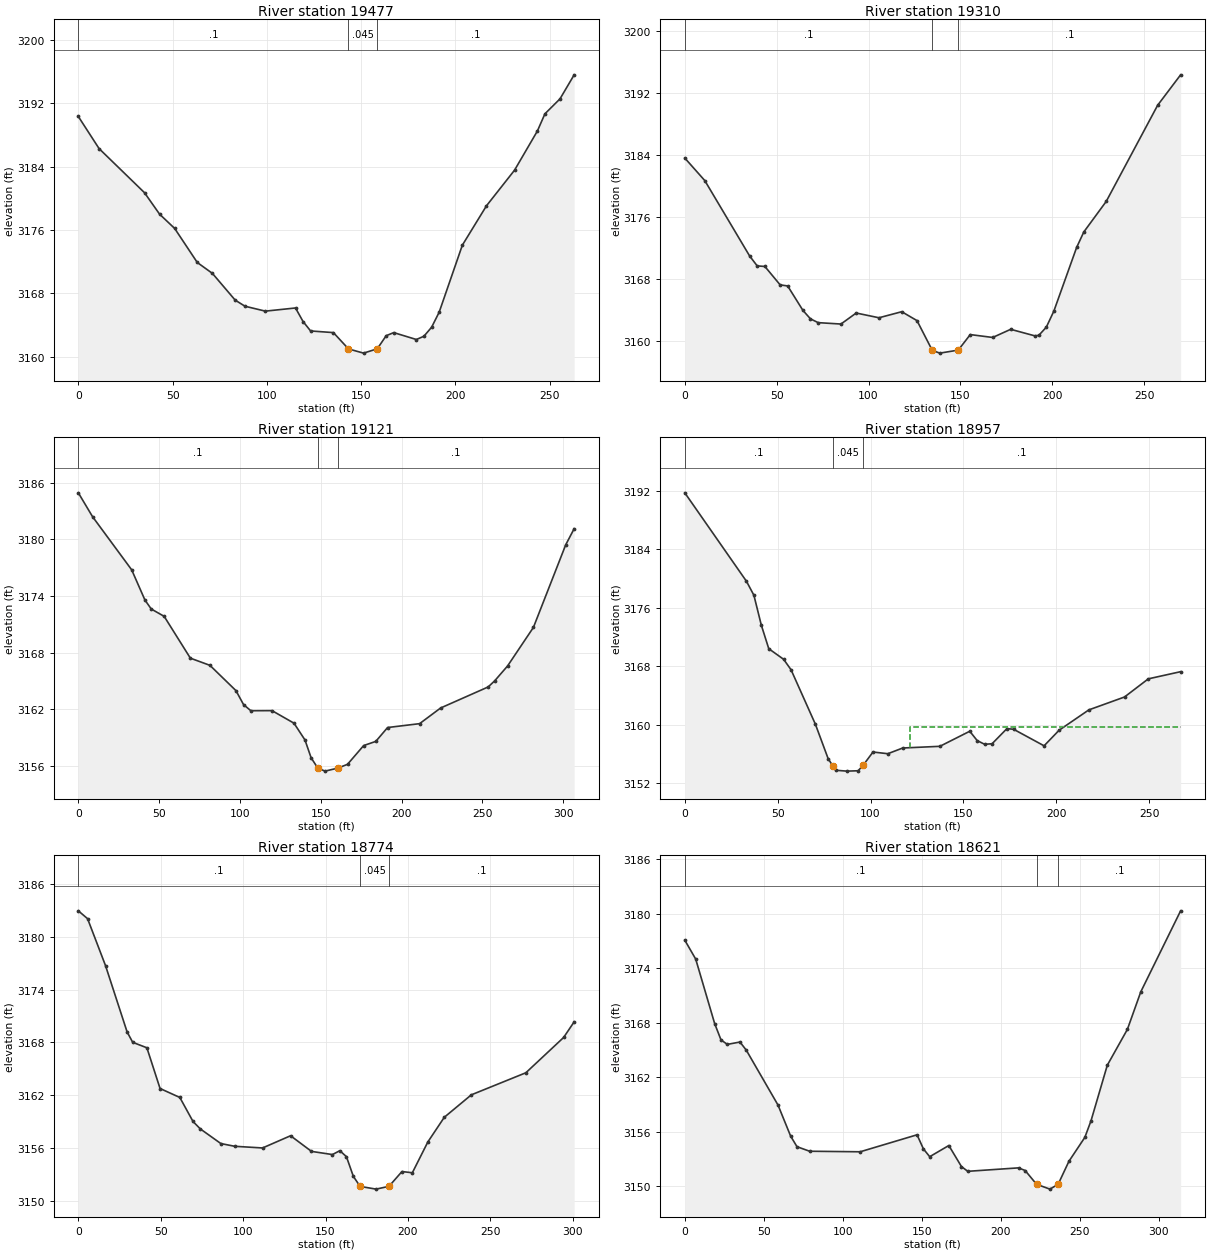
Type RM Length L Ch R = 1 ,19477   ,166.5,167.8,168.8
XS GIS Cut Line= 2
 2230489.1760262616196.924525301 2230751.6897113616213.186434997
#Sta/Elev= 30
       0 3190.32      11 3186.27    35.1  3180.7    43.1 3177.99    51.1 3176.19
    63.1 3171.89    71.1 3170.52    83.2 3167.14    88.4 3166.37    99.2 3165.75
   115.2 3166.15   119.2 3164.44   123.2 3163.25   135.3 3163.04   143.3 3160.98
   151.3 3160.45  158.563160.995   163.3 3162.65   167.3 3163.04   179.3 3162.17
   183.3 3162.58   187.4 3163.72   191.4 3165.62   203.7 3174.08   216.5 3179.05
   231.4 3183.55   243.5 3188.49   247.5 3190.66   255.5 3192.55     263 3195.58
#Mann= 3 ,-1,0
       0      .1       0   143.3    .045       0  158.56      .1       0
Bank Sta=143.3,158.56
XS Rating Curve= 0 ,0
Exp/Cntr(USF)=0,0
Exp/Cntr=0.3,0.1

Type RM Length L Ch R = 1 ,19310   ,186,189,190.6
XS GIS Cut Line= 3
2230462.07284337616309.9835165222230667.28265621616364.964258829
2230724.58652847616368.836142089
#Sta/Elev= 30
       0 3183.64    10.9 3180.73    35.3 3171.01    39.4 3169.74    43.6 3169.66
    51.9 3167.29      56 3167.15    64.3    3164    68.4 3162.91    72.6 3162.42
      85 3162.24    93.3 3163.66   105.7 3163.05   118.1 3163.83   126.4 3162.68
   134.7 3158.85   138.8 3158.49  148.853158.878   155.4 3160.88   167.6 3160.51
   177.4 3161.56   190.5 3160.72   192.7 3160.78   196.8 3161.84   200.9 3163.91
   213.3 3172.12   217.2 3174.11   229.4 3178.05   257.4 3190.45   269.9 3194.37
#Mann= 3 ,-1,0
       0      .1       0   134.7    .045       0  148.85      .1       0
Bank Sta=134.7,148.85
XS Rating Curve= 0 ,0
Exp/Cntr(USF)=0,0
Exp/Cntr=0.3,0.1

Type RM Length L Ch R = 1 ,19121   ,168.8,163.6,160.4
XS GIS Cut Line= 4
2230395.47645128 616464.084470312230493.41207591616476.775035071
2230610.92777787616562.5328919332230673.41013931616561.623482759
#Sta/Elev= 30
       0 3184.93     8.8  3182.4      33 3176.77    41.2 3173.57    45.1 3172.62
    53.1 3171.84    69.3 3167.41    81.4 3166.65    97.5 3163.97   102.2 3162.49
   106.7 3161.84   119.8 3161.85   133.4 3160.52   140.2 3158.74     144 3156.85
148.15413155.756   152.6 3155.44   160.5 3155.76   166.5 3156.16   176.5 3158.15
     184 3158.59   191.3 3160.06   211.1 3160.47   224.1 3162.13   253.5 3164.36
   257.5    3165   265.5 3166.58   281.5 3170.67   301.5 3179.43   306.7 3181.13
#Mann= 3 ,-1,0
       0      .1       0148.1541    .045       0   160.5      .1       0
Bank Sta=148.1541,160.5
XS Rating Curve= 0 ,0
Exp/Cntr(USF)=0,0
Exp/Cntr=0.3,0.1

Type RM Length L Ch R = 1 ,18957   ,186,182.7,179.6
XS GIS Cut Line= 2
2230383.08642485616649.9348668382230649.47199321616666.196776534
#Sta/Elev= 30
       0 3191.69    33.2  3179.6    37.2 3177.69    41.2  3173.6    45.2 3170.39
    53.2 3168.94    57.2 3167.51    70.3 3160.07    77.2 3155.34    79.6 3154.41
    81.2 3153.78    87.2 3153.66    93.3 3153.71    95.9 3154.43   101.3 3156.27
   109.3 3156.04   117.3 3156.82   137.3 3157.05   153.4 3159.11   157.4 3157.83
   161.4 3157.33   165.4  3157.4   173.4 3159.47     177 3159.38   193.4 3157.12
   201.5 3159.25   217.5 3162.03   236.7 3163.79   249.5 3166.27   266.9 3167.25
#Mann= 3 ,-1,0
       0      .1       0    79.6    .045       0    95.9      .1       0
#XS Ineff= 2 , 0
                           121.1         3159.72
Permanent Ineff=
       F       F
Bank Sta=79.6,95.9
XS Rating Curve= 0 ,0
Exp/Cntr(USF)=0,0
Exp/Cntr=0.3,0.1

Type RM Length L Ch R = 1 ,18774   ,152.2,153.3,156
XS GIS Cut Line= 4
2230374.56828168616843.5290298872230447.35968698616845.852159844
2230595.26562755616793.9689241472230666.50827955616790.871417538
#Sta/Elev= 30
       0 3182.95     5.6 3182.06    16.5 3176.72    29.6 3169.18      33    3168
    41.6 3167.38    49.6 3162.75    61.6 3161.73    69.6    3159      74 3158.16
    86.5 3156.49    94.9 3156.18   111.8 3155.99   128.8 3157.38   141.5  3155.6
   154.2 3155.24   158.7 3155.68   162.7    3155   166.9 3152.76     171 3151.62
   180.7 3151.31  188.543151.629   196.4 3153.31   202.7 3153.17   212.1 3156.67
   222.1 3159.48   238.5 3162.03   271.6 3164.54   294.5 3168.55   300.9 3170.33
#Mann= 3 ,-1,0
       0      .1       0     171    .045       0  188.54      .1       0
Bank Sta=171,188.54
XS Rating Curve= 0 ,0
Exp/Cntr(USF)=0,0
Exp/Cntr=0.3,0.1

Type RM Length L Ch R = 1 ,18621   ,249.6,246.6,244.5
XS GIS Cut Line= 3
2230389.28143807616927.9360849772230652.56949981 616939.55173476
 2230699.8064756616922.515448412
#Sta/Elev= 30
       0 3177.09     6.9 3175.01    18.9 3167.91    22.9 3166.12    26.9 3165.62
    34.9 3165.88    38.9 3164.99      59 3158.94      67 3155.52      71 3154.36
      79 3153.86     111  3153.8     147 3155.67     151 3154.12     155 3153.26
   167.1 3154.49   175.1 3152.17   179.1 3151.65   211.2 3152.03   215.4 3151.74
  222.623150.224   231.1 3149.69   236.3 3150.23   243.1 3152.75   253.2 3155.39
   257.1 3157.22   267.4 3163.33   280.1 3167.27   288.6 3171.41   313.8 3180.32
#Mann= 3 ,-1,0
       0      .1       0  222.62    .045       0   236.3      .1       0
Bank Sta=222.62,236.3
XS Rating Curve= 0 ,0
Exp/Cntr(USF)=0,0
Exp/Cntr=0.3,0.1

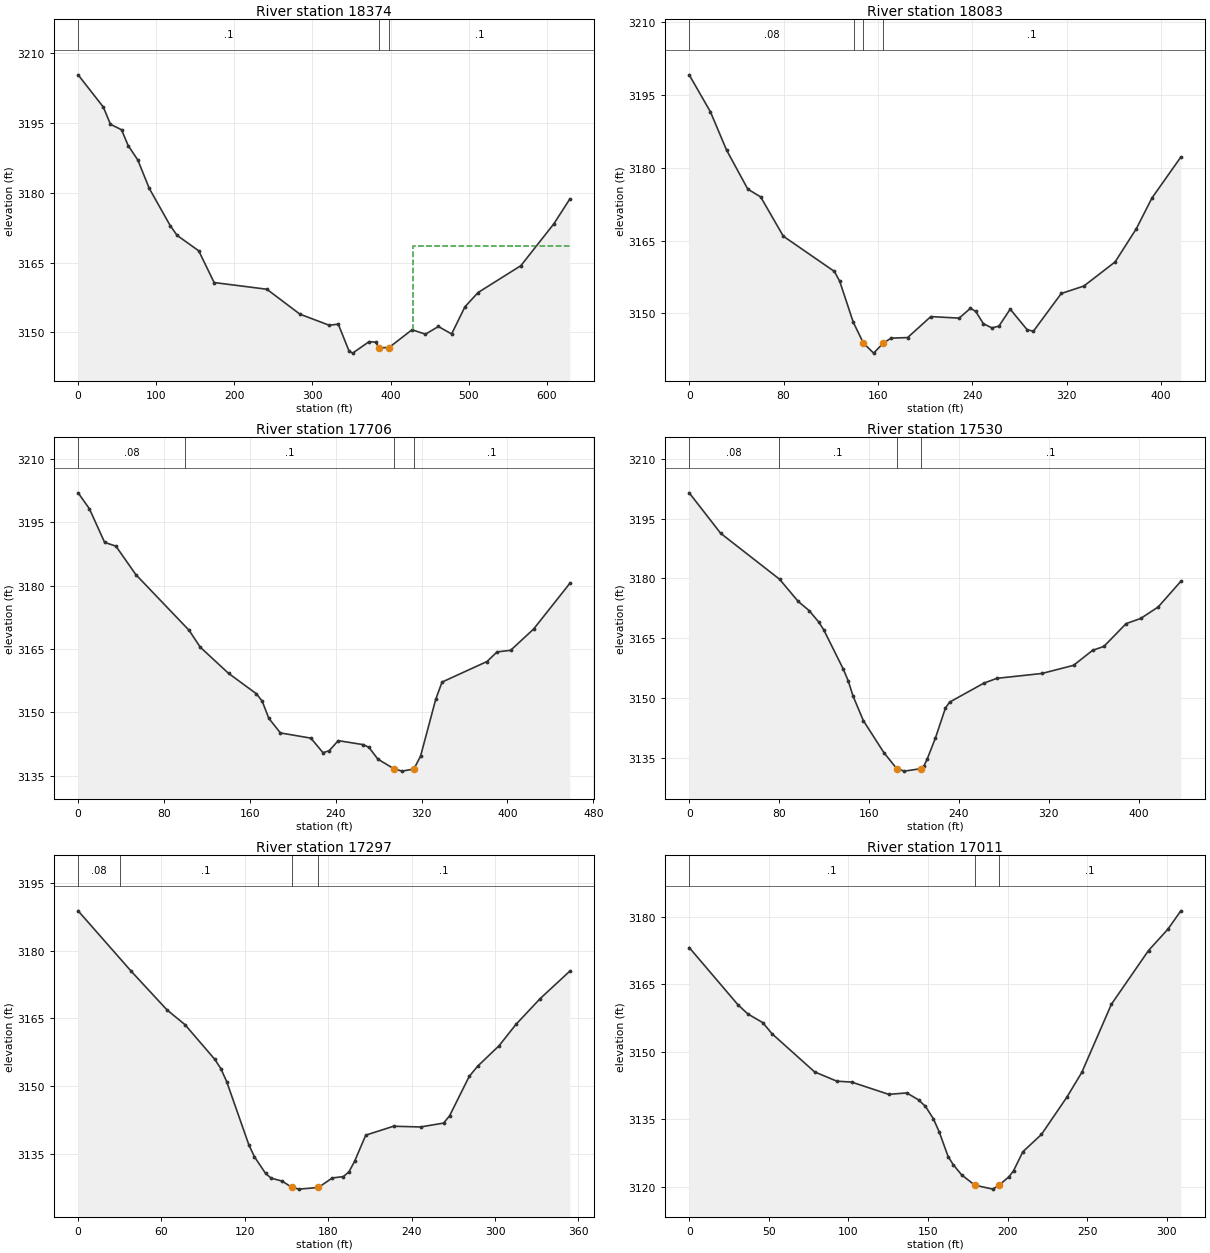
Type RM Length L Ch R = 1 ,18374   ,294.4,291.5,284.5
XS GIS Cut Line= 3
2230241.65030342617377.7869988792230329.03018257617211.708227544
2230747.44293986617070.358627452
#Sta/Elev= 30
       0 3205.32    32.3 3198.39    41.4  3194.7    55.6 3193.52      64 3190.14
    76.4 3187.03    91.1 3180.92   117.8 3172.96   126.7 3170.84   154.4 3167.52
   174.1 3160.71   241.6 3159.27   283.9 3153.92   321.5 3151.53     333 3151.78
   346.8 3145.99   351.4 3145.55   372.5 3148.02     381 3147.89  384.883146.722
397.84513146.737   427.4 3150.57   444.6 3149.62   461.2 3151.27   478.1 3149.66
   495.1 3155.49   511.9 3158.56   566.7 3164.33     609 3173.33   629.3 3178.63
#Mann= 3 ,-1,0
       0      .1       0  384.88    .045       0397.8451      .1       0
#XS Ineff= 2 , 0
                          428.59          3168.6
Permanent Ineff=
       F       F
Bank Sta=384.88,397.8451
XS Rating Curve= 0 ,0
Exp/Cntr(USF)=0,0
Exp/Cntr=0.3,0.1

Type RM Length L Ch R = 1 ,18083   ,373,376.4,378.8
XS GIS Cut Line= 2
2230581.67101521 617479.579067512230813.12359237617132.830411025
#Sta/Elev= 30
       0 3199.18      18 3191.55    31.7 3183.65    49.7  3175.6    60.6    3174
    79.8  3165.9   123.1 3158.63   127.6 3156.62   139.1 3148.17   147.7 3143.86
   156.4 3141.78  164.533143.835   171.2 3144.87   185.2 3144.99   204.9 3149.32
   228.9    3149   238.5 3151.03   242.9  3150.4   249.5 3147.84   256.7 3146.99
   262.6 3147.34   272.2 3150.85   286.6  3146.6   291.9 3146.31   315.5 3154.08
   334.7 3155.62   361.2  3160.6   379.2 3167.46   392.4 3173.77   416.9 3182.22
#Mann= 4 ,-1,0
       0     .08       0     140      .1       0   147.7    .045       0
  164.53      .1       0
Bank Sta=147.7,164.53
XS Rating Curve= 0 ,0
Exp/Cntr(USF)=0,0
Exp/Cntr=0.3,0.1

Type RM Length L Ch R = 1 ,17706   ,177.6,176.5,176.6
XS GIS Cut Line= 3
2230781.28810778617575.9459397842231072.10956161617329.866248085
2231101.36379069617258.451512382
#Sta/Elev= 30
       0 3201.96    10.5 3198.19    24.7 3190.22    35.2 3189.34    53.8 3182.59
   103.4  3169.4   113.8 3165.41   140.2  3159.2   166.2 3154.36   171.5 3152.63
   177.7 3148.55   188.5  3145.1   216.9 3143.86   228.2 3140.41   233.9 3140.88
   242.4 3143.27   265.8 3142.32     271 3141.68   279.3 3138.89  294.633136.554
     302 3136.05   312.9 3136.56   319.1 3139.61   333.2 3153.05   339.1 3157.14
     381 3162.01   390.4 3164.29     403 3164.66   424.5 3169.72   458.1  3180.5
#Mann= 4 ,-1,0
       0     .08       0     100      .1       0  294.63    .045       0
   312.9      .1       0
Bank Sta=294.63,312.9
XS Rating Curve= 0 ,0
Exp/Cntr(USF)=0,0
Exp/Cntr=0.3,0.1

Type RM Length L Ch R = 1 ,17530   ,242.6,232.9,224.7
XS GIS Cut Line= 4
2231005.39012421617702.8586199012231066.76704214617562.135507438
2231126.01943922617510.4826874042231249.69406268617346.471539765
#Sta/Elev= 30
       0 3201.43      28  3191.3    80.4  3179.8      97 3174.24   106.7 3171.96
   115.3 3169.08   119.7 3167.14   137.2 3157.26   141.5 3154.37   145.8 3150.55
     155 3144.39   173.2 3136.41  184.73 3132.37   191.5 3131.76   206.2 3132.38
   209.1 3133.16   211.9 3134.86   219.1 3140.05     228 3147.53   231.7 3149.03
   262.3  3153.8   273.8 3154.99   313.9 3156.21     342 3158.24     359 3162.01
     369 3162.97   388.8 3168.69   401.8 3169.98   417.4 3172.87   437.5 3179.28
#Mann= 4 ,-1,0
       0     .08       0      80      .1       0  184.73    .045       0
   206.2      .1       0
Bank Sta=184.73,206.2
XS Rating Curve= 0 ,0
Exp/Cntr(USF)=0,0
Exp/Cntr=0.3,0.1

Type RM Length L Ch R = 1 ,17297   ,280.7,285.8,289.7
XS GIS Cut Line= 4
2231267.42456166617756.6338252972231306.14339427617659.406534521
2231300.12046475617500.2291115692231335.39762335617417.628935334
#Sta/Elev= 30
       0 3188.82    38.2 3175.45      64 3166.88    76.9 3163.63    98.4 3155.93
   102.7  3153.9   106.9 3151.03   122.9    3137   126.9 3134.38   134.9  3130.7
   138.9 3129.65   146.9 3128.99  153.773127.605   158.9 3127.22   172.93127.585
   182.9 3129.69   190.9    3130   194.9 3131.05   198.9 3133.34     207 3139.17
     227 3141.14   246.4 3140.98     263 3141.84   267.3 3143.44   281.5  3152.2
   287.6 3154.46   302.9 3158.95   315.1 3163.69   332.5 3169.39   353.8 3175.46
#Mann= 4 ,-1,0
       0     .08       0      30      .1       0  153.77    .045       0
   172.9      .1       0
Bank Sta=153.77,172.9
XS Rating Curve= 0 ,0
Exp/Cntr(USF)=0,0
Exp/Cntr=0.3,0.1

Type RM Length L Ch R = 1 ,17011   ,186.8,186.3,185.6
XS GIS Cut Line= 2
2231464.46039872  617792.77140242231622.77740317617527.762503647
#Sta/Elev= 30
       0 3173.12    30.6 3160.41    36.8 3158.37    46.2 3156.43      52 3153.97
    78.7  3145.5    92.7 3143.43     102 3143.23   125.3  3140.5   136.6 3140.82
     144 3139.28   148.3 3137.85   153.3  3135.1     157 3132.15   162.6 3126.67
   165.8 3124.88     171 3122.64   179.33120.337   190.6 3119.45   194.4 3120.28
   200.8 3122.21   203.7 3123.56   209.5 3127.75   221.2 3131.61   237.2 3139.91
   246.5 3145.37   265.1 3160.52   288.4 3172.45   300.6  3177.2   308.7 3181.27
#Mann= 3 ,-1,0
       0      .1       0   179.3    .045       0   194.4      .1       0
Bank Sta=179.3,194.4
XS Rating Curve= 0 ,0
Exp/Cntr(USF)=0,0
Exp/Cntr=0.3,0.1