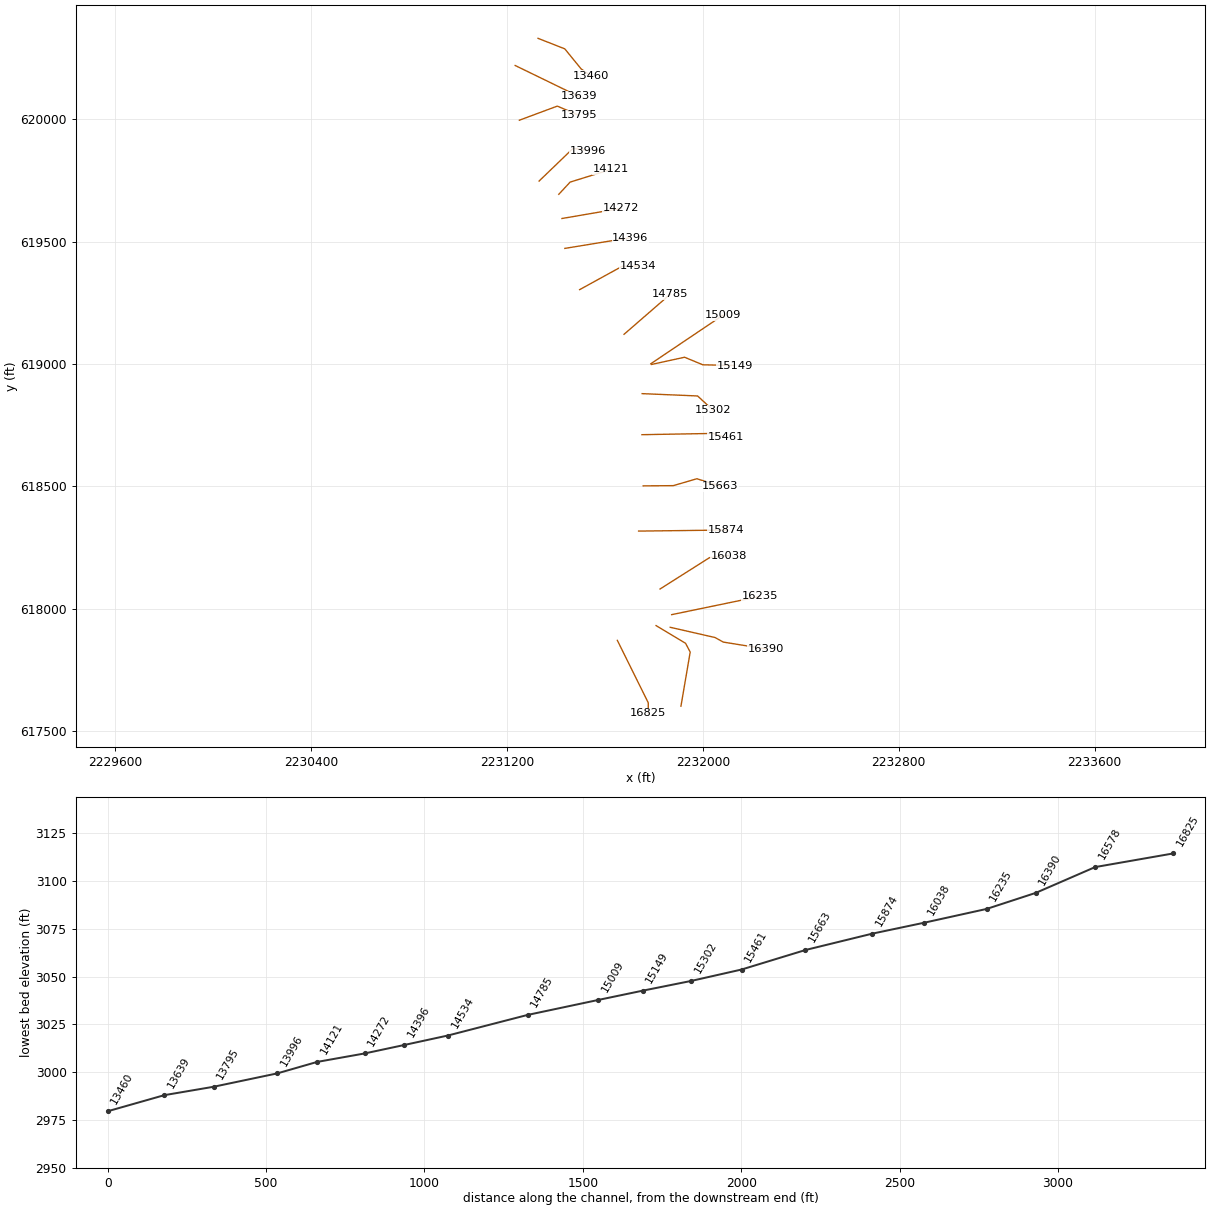
HEC-RAS study ROCKYRN.prj: ROCKYRN

--- ROCKYRN.g01 (geometry) --- (continued)

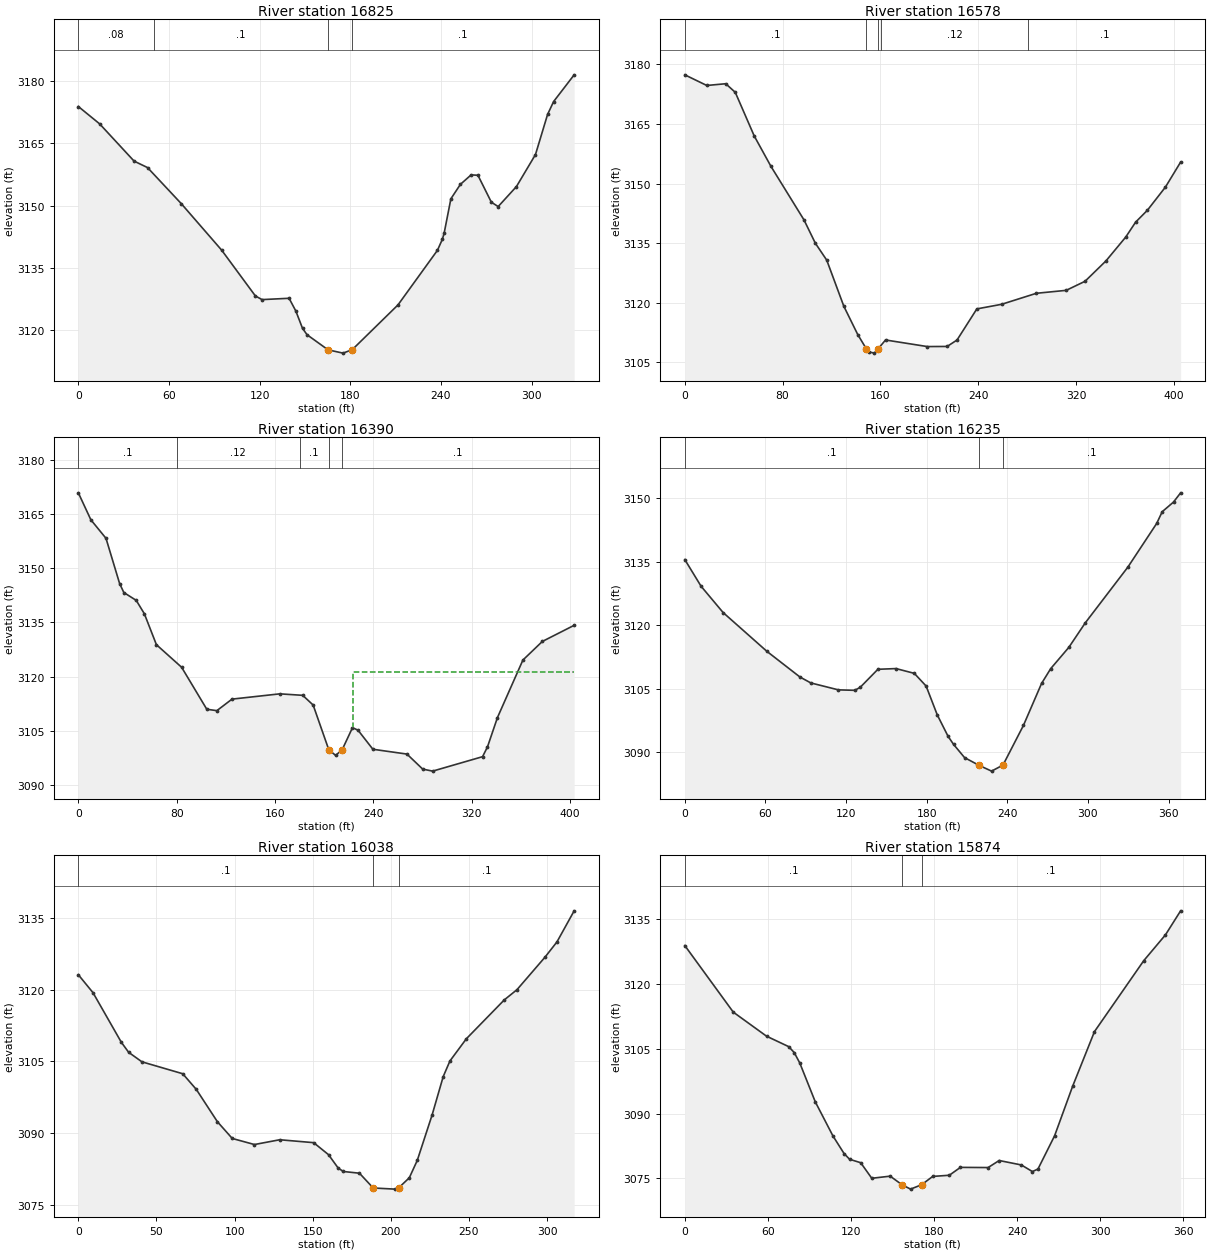
Type RM Length L Ch R = 1 ,16825   ,247.2,247.3,248.2
XS GIS Cut Line= 3
2231650.31079525617870.2090676192231776.79231511617614.664772394
2231776.79231511617571.643847271
#Sta/Elev= 30
       0 3173.91    14.1 3169.73    36.9 3160.76    45.8  3159.2    68.1 3150.53
    94.9  3139.3   117.2 3128.28   121.6  3127.4   139.5 3127.72     144 3124.63
   148.4 3120.47   151.4 3118.94   165.33115.302   175.2 3114.51   181.3 3115.34
   211.6 3126.13   237.7 3139.27     241 3141.96   242.2 3143.51   246.6 3151.68
   252.9 3155.16     260 3157.44   264.5 3157.35   273.4 3150.86   277.9 3149.81
     290 3154.63   302.6 3162.34   310.6 3171.99   314.6  3175.1   328.2 3181.54
#Mann= 4 ,-1,0
       0     .08       0      50      .1       0   165.3    .045       0
   181.3      .1       0
Bank Sta=165.3,181.3
XS Rating Curve= 0 ,0
Exp/Cntr(USF)=0,0
Exp/Cntr=0.3,0.1

Type RM Length L Ch R = 1 ,16578   ,181.6,187.6,188.4
XS GIS Cut Line= 4
 2231808.6277997 617930.438362792231929.08639004617858.072655851
2231948.00452807617822.3703251232231910.15718299617600.898076355
#Sta/Elev= 30
       0 3177.39      18 3174.71    33.5 3175.15    41.3 3172.98    56.8    3162
    70.5 3154.34    97.5 3140.88   106.8 3135.01   116.1 3130.76   130.1 3119.14
   141.5 3112.01  148.42 3108.47   150.6 3107.66   155.1 3107.35   158.3 3108.49
   164.2 3110.66   198.4    3109   214.6 3109.03   222.7 3110.65   238.9 3118.48
   259.2 3119.64   287.6 3122.41     312 3123.15   327.4 3125.43   344.5 3130.55
   360.7 3136.56   368.8 3140.32   378.4  3143.3   393.2 3149.15   405.6 3155.43
#Mann= 5 ,-1,0
       0      .1       0  148.42    .045       0   158.3      .1       0
  160.52     .12       0  280.93      .1       0
Bank Sta=148.42,158.3
XS Rating Curve= 0 ,0
Exp/Cntr(USF)=0,0
Exp/Cntr=0.3,0.1

Type RM Length L Ch R = 1 ,16390   ,148.6,155,159.2
XS GIS Cut Line= 4
2231866.27583936617923.5550147712232049.64095966617881.654615047
2232083.05859291617863.0509841712232257.76625797617834.931909019
#Sta/Elev= 30
       0 3170.87    10.2  3163.4    22.5 3158.28    33.6 3145.74      37 3143.28
    47.1  3141.1    53.7  3137.4    63.5 3128.84      84 3122.59   104.5 3110.96
   112.7 3110.58     125 3113.77   163.9 3115.23   182.5 3114.82     191 3112.13
   203.7 3099.78   209.3 3098.19  214.64 3099.79     223 3105.87   227.5 3105.17
   239.6 3099.89   267.3 3098.56   280.1  3094.4   288.2 3093.84   328.8 3097.84
   332.8 3100.55   340.9 3108.66   361.6 3124.58   377.4 3129.73   403.3  3134.2
#Mann= 5 ,-1,0
       0      .1       0      80     .12       0     180      .1       0
   203.7    .045       0  214.64      .1       0
#XS Ineff= 2 , 0
                          223.16         3121.16
Permanent Ineff=
       F       F
Bank Sta=203.7,214.64
XS Rating Curve= 0 ,0
Exp/Cntr(USF)=0,0
Exp/Cntr=0.3,0.1

Type RM Length L Ch R = 1 ,16235   ,193.1,196.9,199.6
XS GIS Cut Line= 2
2231872.29876888617975.180124917 2232233.6745399 618050.03653463
#Sta/Elev= 30
       0 3135.54    12.1 3129.23    28.5    3123    61.1 3113.81    85.7 3107.73
    93.8 3106.33   114.3 3104.69   126.5 3104.58   130.6 3105.31   143.7 3109.56
   157.2 3109.73   170.8  3108.6   179.6 3105.59   187.9 3098.76   195.9 3093.71
     200 3091.79   208.2 3088.65   218.8 3086.85   228.3 3085.45   236.8 3086.88
     252 3096.26   265.5  3106.2   272.3 3109.71   285.8 3114.75   298.1 3120.58
   329.8 3133.78   351.2  3144.1   355.3 3146.87   363.7 3149.15     369 3151.34
#Mann= 3 ,-1,0
       0      .1       0   218.8    .045       0   236.8      .1       0
Bank Sta=218.8,236.8
XS Rating Curve= 0 ,0
Exp/Cntr(USF)=0,0
Exp/Cntr=0.3,0.1

Type RM Length L Ch R = 1 ,16038   ,168.2,163.8,160.8
XS GIS Cut Line= 3
2231824.97575124618080.1511822152232027.17409932618208.353539079
2232104.61176454618216.957724104
#Sta/Elev= 30
       0  3123.1     9.4 3119.34    27.5 3108.98    32.2 3106.87    40.7 3104.88
    66.8 3102.39    75.5 3099.11      89 3092.35    98.5 3088.85   112.7 3087.58
   128.9 3088.58   150.6 3087.97   160.1 3085.46   166.3 3082.65   169.6 3081.94
   179.9 3081.58   188.7 3078.49   202.7 3078.25  204.913078.494   211.8 3080.62
   216.9 3084.26   226.4 3093.77   233.5 3101.79   237.8 3105.06   248.3  3109.7
   272.6 3117.84   280.7 3119.97   298.5 3126.72   306.3 3129.97   317.3 3136.47
#Mann= 3 ,-1,0
       0      .1       0   188.7    .045       0  204.91      .1       0
Bank Sta=188.7,204.91
XS Rating Curve= 0 ,0
Exp/Cntr(USF)=0,0
Exp/Cntr=0.3,0.1

Type RM Length L Ch R = 1 ,15874   ,202.3,211.2,212.7
XS GIS Cut Line= 2
  2231737.213064618316.7662703872232095.14716101618321.068362899
#Sta/Elev= 30
       0 3128.87      35 3113.47      59 3107.91      75 3105.49      79 3104.12
      83 3101.72    94.2 3092.73     107 3084.81     115 3080.76     119 3079.43
     127 3078.64     135 3075.04   148.3 3075.53   156.83073.554     163 3072.53
     171 3073.55     179 3075.47     191 3075.74     199 3077.56     219 3077.52
     227 3079.15     243 3078.12     251 3076.59     255 3077.18     267 3084.86
     280  3096.3   295.8 3108.97   331.4 3125.38     347 3131.32     358  3136.9
#Mann= 3 ,-1,0
       0      .1       0   156.8    .045       0     171      .1       0
Bank Sta=156.8,171
XS Rating Curve= 0 ,0
Exp/Cntr(USF)=0,0
Exp/Cntr=0.3,0.1

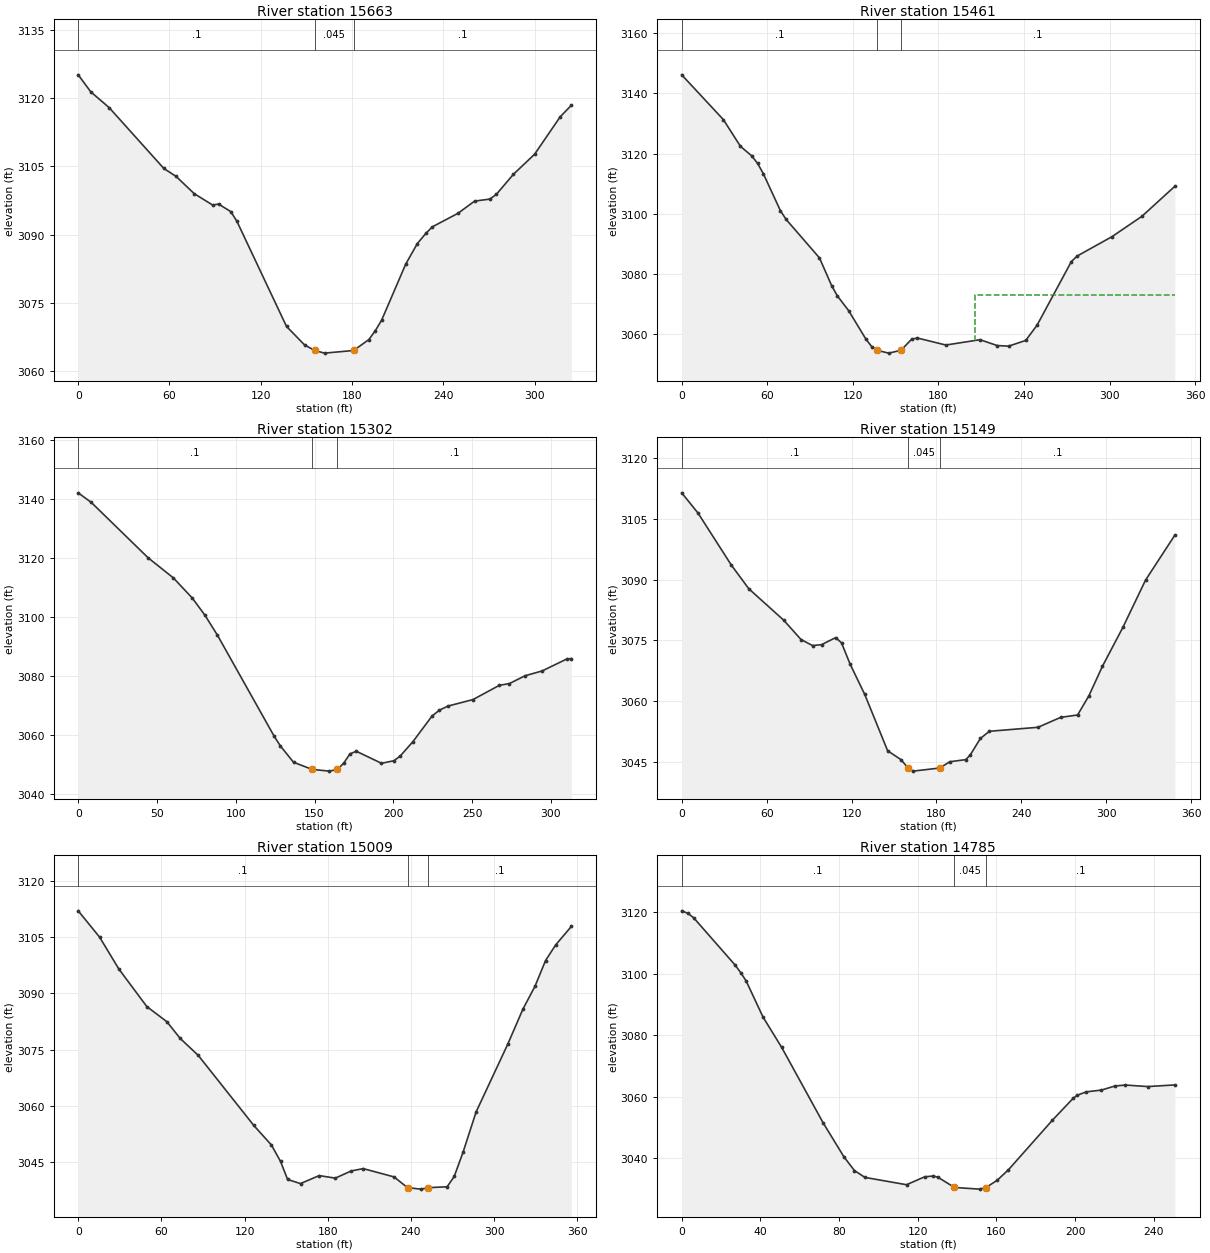
Type RM Length L Ch R = 1 ,15663   ,205.6,201.9,199.7
XS GIS Cut Line= 4
2231755.86201073618501.6147846462231879.13198964618502.589864064
2231975.41019262 618530.78912987 2232071.1955731618500.275062987
#Sta/Elev= 30
       0 3125.11     8.3 3121.36    20.3 3117.92    56.3 3104.53    64.3  3102.8
    76.3 3098.99    88.3 3096.51    92.3 3096.71   100.3 3095.05   104.3 3092.93
   136.9 3069.83   148.8 3065.75  155.49 3064.54   161.9 3063.96     181 3064.54
     191 3066.93   195.2 3068.85   199.4 3071.19   215.3 3083.55   222.9 3088.04
   228.6 3090.31   232.8 3091.72   249.6 3094.68   260.5 3097.36   270.6 3097.81
   274.8 3098.84     286 3103.24     300 3107.68   316.8  3115.9   324.1 3118.41
#Mann= 3 ,-1,0
       0      .1       0  155.49    .045       0     181      .1       0
Bank Sta=155.49,181
XS Rating Curve= 0 ,0
Exp/Cntr(USF)=0,0
Exp/Cntr=0.3,0.1

Type RM Length L Ch R = 1 ,15461   ,160,159.1,158.9
XS GIS Cut Line= 3
2231750.97976003618710.8379445062232040.94079536618716.000455521
2232094.28674251618699.652503975
#Sta/Elev= 30
       0 3146.19    29.2 3131.32    41.2 3122.43    49.2 3119.23    53.2 3116.77
    57.2 3113.39    69.2 3101.08    73.2 3098.16    96.6 3085.38   105.2 3076.09
   109.2 3072.72     117 3067.89   129.2 3058.37   133.2 3055.91   136.93054.671
   145.2 3053.74  153.783054.688   161.2 3058.36   165.2 3058.77   185.2 3056.43
   209.2  3058.2   221.2 3056.26   229.2 3056.06   241.2 3057.95   249.2 3063.03
   273.2 3084.13   277.2 3085.97   301.8 3092.45   322.7 3099.19   345.8 3109.16
#Mann= 3 ,-1,0
       0      .1       0   136.9    .045       0  153.78      .1       0
#XS Ineff= 2 , 0
                           205.6         3073.07
Permanent Ineff=
       F       F
Bank Sta=136.9,153.78
XS Rating Curve= 0 ,0
Exp/Cntr(USF)=0,0
Exp/Cntr=0.3,0.1

Type RM Length L Ch R = 1 ,15302   ,155.6,152.9,149.5
XS GIS Cut Line= 3
2231751.84017854618878.6195524832231978.13024468618869.154948956
2232041.80121386 618810.64649079
#Sta/Elev= 30
       0 3142.22     8.3 3138.97    44.4 3120.16    60.4 3113.35    72.4 3106.52
    80.4 3100.72    88.4 3093.89   124.4  3059.6   128.4 3056.26   136.7 3050.77
   148.5 3048.36   159.3 3047.77   164.5 3048.33   168.5 3050.46   172.5 3053.62
   176.5 3054.52   192.5 3050.43   200.5 3051.31   204.5 3052.96   212.5 3057.81
   224.6 3066.48   229.3 3068.47   234.7 3069.85   250.6 3072.06   267.3 3076.89
   273.7 3077.49   283.6 3080.13   294.5 3081.78     310  3085.8     313 3085.97
#Mann= 3 ,-1,0
       0      .1       0   148.5    .045       0   164.5      .1       0
Bank Sta=148.5,164.5
XS Rating Curve= 0 ,0
Exp/Cntr(USF)=0,0
Exp/Cntr=0.3,0.1

Type RM Length L Ch R = 1 ,15149   ,130.6,140.2,146
XS GIS Cut Line= 4
2231789.84591102618997.864101566 2231924.9905286619027.395330254
2231999.56686906618996.5283023832232128.85080098618993.562009053
#Sta/Elev= 30
       0  3111.5    11.5 3106.51      35 3093.66    47.4 3087.78    72.1 3079.99
    84.3 3075.22    92.5 3073.72    98.8 3073.96   108.8  3075.7   112.9  3074.4
     119 3069.12   129.3 3061.66   145.5 3047.71   154.8 3045.55  160.03 3043.44
   163.4 3042.68   182.3 3043.45   189.4    3045   200.6 3045.52   203.7 3046.59
     211 3050.75   217.3 3052.53   251.7 3053.52   267.7 3055.97   279.7 3056.57
   287.7 3061.33   297.2 3068.58   311.7 3078.24   327.7 3089.92   348.4 3101.04
#Mann= 3 ,-1,0
       0      .1       0  160.03    .045       0   182.3      .1       0
Bank Sta=160.03,182.3
XS Rating Curve= 0 ,0
Exp/Cntr(USF)=0,0
Exp/Cntr=0.3,0.1

Type RM Length L Ch R = 1 ,15009   ,221.5,223.4,222.9
XS GIS Cut Line= 2
2231787.11733714 619000.798979832232082.24088347619199.555653894
#Sta/Elev= 30
       0    3112    15.4 3105.01    29.3 3096.51    49.5 3086.49      64 3082.44
    73.6 3077.99    86.6 3073.48   126.7  3054.8   139.4  3049.6     146 3045.21
   151.1  3040.4   160.4 3039.31   173.9 3041.44   185.5 3040.76     197 3042.68
   205.6  3043.3   227.9 3041.09   237.6 3038.22   247.2 3037.83  252.513038.216
   266.2 3038.46   271.3 3041.21   277.7  3047.7   287.1 3058.41   309.9 3076.44
   320.9 3085.83   329.6 3091.92   337.2 3098.75   344.4 3102.87   355.8 3107.84
#Mann= 3 ,-1,0
       0      .1       0   237.6    .045       0  252.51      .1       0
Bank Sta=237.6,252.51
XS Rating Curve= 0 ,0
Exp/Cntr(USF)=0,0
Exp/Cntr=0.3,0.1

Type RM Length L Ch R = 1 ,14785   ,252.2,251.3,249.8
XS GIS Cut Line= 2
2231677.84418733619121.2575701722231867.13625786619285.597504139
#Sta/Elev= 30
       0 3120.47     3.1 3119.67       6 3118.26    27.1 3102.88      30 3100.38
    32.8 3097.62    41.3 3085.97    50.8 3076.09    71.9 3051.53    82.5 3040.45
    87.8 3036.03    93.1  3033.8   114.3 3031.41   123.5 3033.99     128 3034.24
   130.2 3033.86  138.673030.525   151.4 3029.98   154.7 3030.49   160.4 3032.87
   166.1 3036.27   188.5 3052.43   199.1 3059.57   201.2 3060.54   205.7 3061.61
   213.4 3062.19   220.3 3063.52   225.6 3063.82   236.9 3063.33   250.7 3063.86
#Mann= 3 ,-1,0
       0      .1       0  138.67    .045       0   154.7      .1       0
Bank Sta=138.67,154.7
XS Rating Curve= 0 ,0
Exp/Cntr(USF)=0,0
Exp/Cntr=0.3,0.1

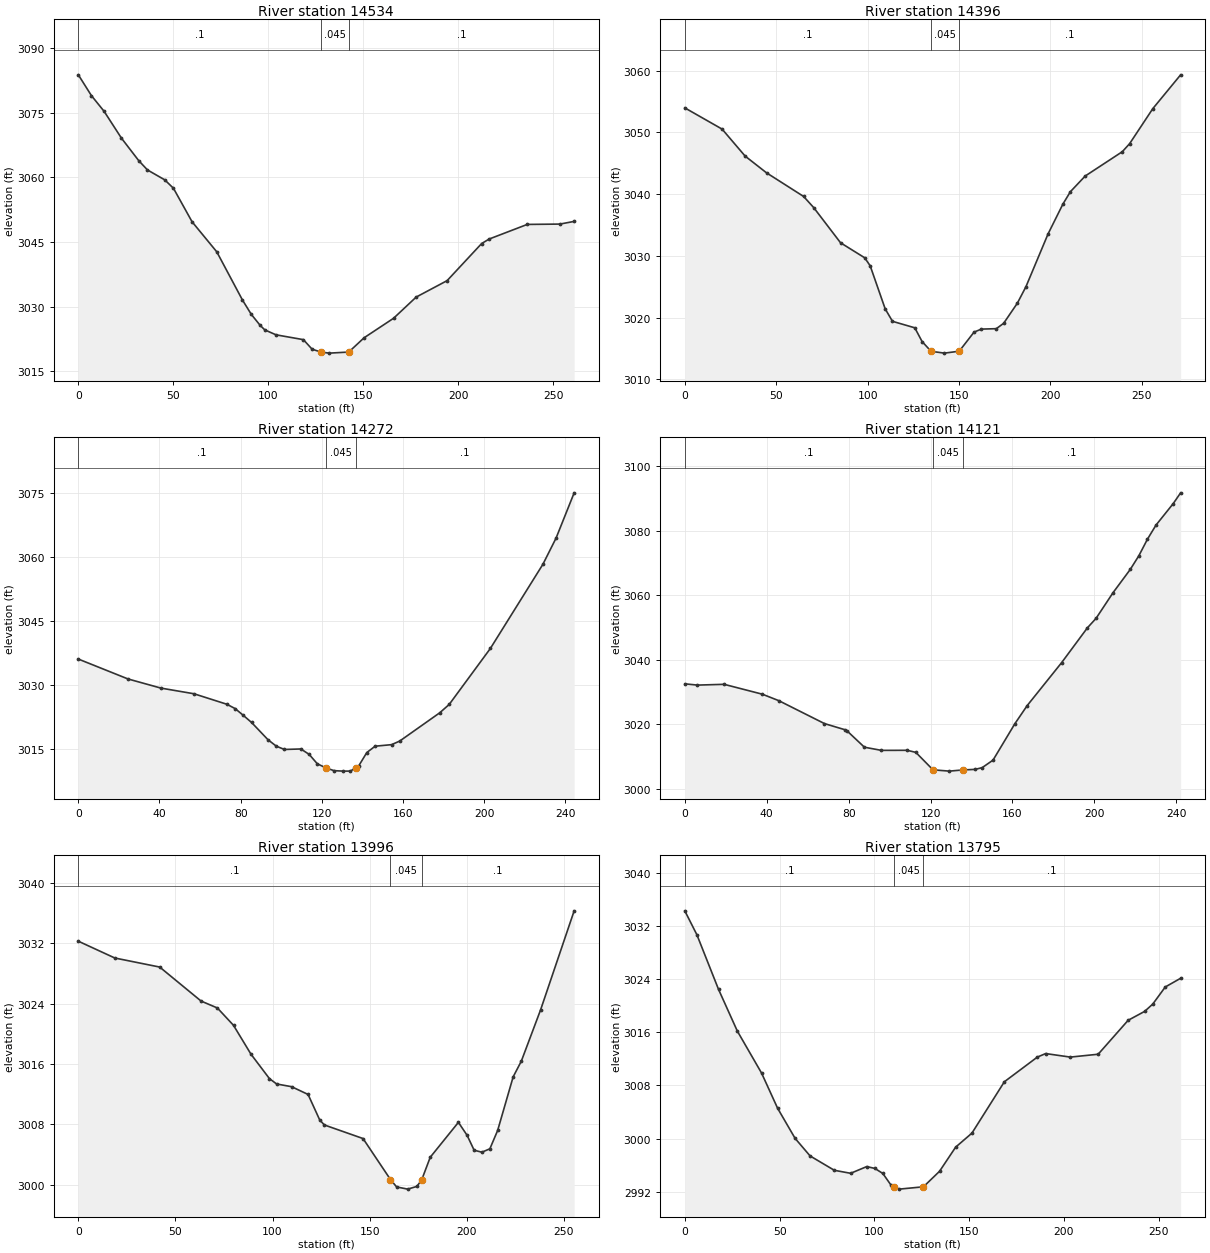
Type RM Length L Ch R = 1 ,14534   ,139.9,138.1,135.3
XS GIS Cut Line= 3
2231496.29588331 619303.66629269 2231670.1004208619399.172746461
2231732.91097148619400.033164964
#Sta/Elev= 30
       0 3083.83     6.9    3079    13.6 3075.34    22.7 3069.13    31.8 3063.91
    36.4 3061.75    45.5 3059.45    50.1 3057.49    59.9 3049.71    72.9 3042.74
    86.4 3031.57    91.1 3028.21    95.7 3025.69    98.2 3024.61   104.1 3023.47
   118.5 3022.35   123.1 3020.14   127.7 3019.47   127.7 3019.46   132.2 3019.22
   142.4 3019.47   150.5 3022.79     166 3027.31   177.9 3032.23   194.2 3036.05
   212.4 3044.67   216.4 3045.72   236.4  3049.1   253.6 3049.18   261.1  3049.8
#Mann= 3 ,-1,0
       0      .1       0   127.7    .045       0   142.4      .1       0
Bank Sta=127.7,142.4
XS Rating Curve= 0 ,0
Exp/Cntr(USF)=0,0
Exp/Cntr=0.3,0.1

Type RM Length L Ch R = 1 ,14396   ,124.3,124.5,124.4
XS GIS Cut Line= 2
2231436.06658814619472.308319169 2231703.6567424619516.189662793
#Sta/Elev= 30
       0 3053.97    20.4 3050.53      33 3046.16    44.7 3043.45      65 3039.62
    70.5 3037.82    85.2 3032.12    98.4 3029.69   101.4 3028.39   109.6 3021.42
   113.6  3019.4   125.8 3018.35   129.8 3016.12  134.713014.545     142 3014.25
   150.1 3014.56   158.2 3017.65   162.2 3018.14   170.4 3018.21   174.4 3019.08
   181.9 3022.34   186.6 3025.01   198.7 3033.56   206.8 3038.38   210.9 3040.39
     219 3042.93   239.3 3046.87   243.3 3048.17     256 3053.85   271.2 3059.32
#Mann= 3 ,-1,0
       0      .1       0  134.71    .045       0   150.1      .1       0
Bank Sta=134.71,150.1
XS Rating Curve= 0 ,0
Exp/Cntr(USF)=0,0
Exp/Cntr=0.3,0.1

Type RM Length L Ch R = 1 ,14272   ,149.1,150.3,151
XS GIS Cut Line= 2
2231424.02072911619594.4877465162231664.93790979619635.787834633
#Sta/Elev= 30
       0 3036.13    24.5 3031.46    40.7 3029.32      57 3027.99    73.2 3025.53
    77.3 3024.51    81.3 3022.93    85.4 3021.25    93.5  3017.2    97.6 3015.69
   101.6 3014.92   109.7 3015.04   113.8 3013.76   117.8 3011.56   121.9 3010.64
     126 3009.95   130.6 3009.84   134.1 3009.85  136.923010.656   138.1 3010.99
   142.2  3014.2   146.3 3015.69   154.4 3016.05   158.4 3016.89   178.1 3023.51
   182.8 3025.48   203.1 3038.62     229 3058.37   235.5 3064.53   244.4 3075.13
#Mann= 3 ,-1,0
       0      .1       0   121.9    .045       0  136.92      .1       0
Bank Sta=121.9,136.92
XS Rating Curve= 0 ,0
Exp/Cntr(USF)=0,0
Exp/Cntr=0.3,0.1

Type RM Length L Ch R = 1 ,14121   ,120.4,125.6,127.7
XS GIS Cut Line= 3
2231411.11445157619693.435874297 2231457.5770507619743.340147438
2231623.63782167619794.965257585
#Sta/Elev= 30
       0 3032.48     6.2 3032.09    19.2 3032.33    37.9 3029.26    45.9 3027.26
    68.2 3020.15    78.1 3018.26    79.3 3017.84    87.7 3012.82      96 3011.84
   108.6 3011.86   112.8 3011.22   121.2  3005.8   129.2  3005.4   135.6 3005.76
   141.7 3005.94   145.2 3006.48   150.5 3008.81   161.2 3020.14   167.2 3025.75
     184 3039.06   196.6 3049.87   200.8 3052.79   209.1 3060.76   217.5 3067.97
   221.7 3072.21   225.9 3077.36   230.1 3081.75   238.5 3088.41   242.1 3091.74
#Mann= 3 ,-1,0
       0      .1       0   121.2    .045       0   135.6      .1       0
Bank Sta=121.2,135.6
XS Rating Curve= 0 ,0
Exp/Cntr(USF)=0,0
Exp/Cntr=0.3,0.1

Type RM Length L Ch R = 1 ,13996   ,205.1,201.2,198.7
XS GIS Cut Line= 3
2231330.62724975619747.5234518022231470.01504714619881.748738183
2231531.10476082619872.284134656
#Sta/Elev= 30
       0  3032.3    18.8 3030.07    41.9 3028.87    63.2 3024.36    71.6 3023.44
    79.9 3021.14    88.9 3017.31    98.4 3014.07   102.1 3013.36   109.8    3013
   118.3 3011.97   124.3 3008.58   126.7 3007.92   146.6 3006.12  160.73 3000.68
   163.9  2999.7   169.6 2999.41   174.3 2999.77   176.8 3000.64   181.2 3003.64
   195.7 3008.27   200.2 3006.54   203.8 3004.57   207.8 3004.31   211.9 3004.76
   215.9 3007.19   223.9 3014.31   228.1 3016.39     238 3023.18   255.3 3036.33
#Mann= 3 ,-1,0
       0      .1       0  160.73    .045       0   176.8      .1       0
Bank Sta=160.73,176.8
XS Rating Curve= 0 ,0
Exp/Cntr(USF)=0,0
Exp/Cntr=0.3,0.1

Type RM Length L Ch R = 1 ,13795   ,164.1,155.8,150.1
XS GIS Cut Line= 3
2231250.21619161619996.3031871572231405.09152205 620053.95122682
 2231493.7146278620016.092812713
#Sta/Elev= 30
       0 3034.24     6.4 3030.63    17.8 3022.43    27.7 3016.17    40.5 3009.85
      49 3004.54    58.2 3000.03    66.1 2997.39    78.9 2995.23    87.5 2994.78
      96 2995.79   100.3 2995.51   104.5 2994.75   108.8    2993   110.6 2992.73
   113.1  2992.4   125.9 2992.75   134.4 2995.08   142.9 2998.71   151.5 3000.82
   168.6 3008.54     186 3012.25   190.4 3012.78   203.4 3012.25   218.1 3012.68
   233.9 3017.78   242.6 3019.12   246.9 3020.22   253.5 3022.79   261.6  3024.1
#Mann= 3 ,-1,0
       0      .1       0   110.6    .045       0   125.9      .1       0
Bank Sta=110.6,125.9
XS Rating Curve= 0 ,0
Exp/Cntr(USF)=0,0
Exp/Cntr=0.3,0.1

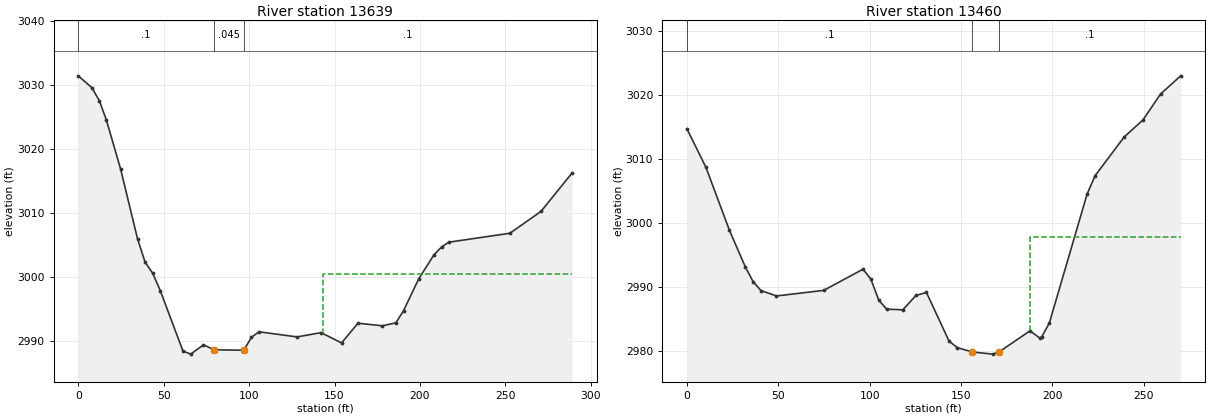
Type RM Length L Ch R = 1 ,13639   ,183.1,178.5,174.7
XS GIS Cut Line= 2
2231233.00782156620220.011997792 2231492.8542093620093.530477933
#Sta/Elev= 30
       0  3031.5       8 3029.64    12.4 3027.59    16.5 3024.57    24.8 3016.93
    34.7 3006.03    39.1  3002.4    43.6 3000.63      48 2997.93    61.3 2988.48
    65.8    2988    73.3 2989.45    79.6 2988.68    96.9 2988.61   101.4 2990.63
   105.8 2991.49   128.1 2990.69   142.1 2991.36   154.1 2989.75   163.7 2992.83
     178 2992.43   185.9 2992.89   190.4  2994.8   199.3 2999.78   208.2 3003.52
   212.6 3004.74   216.9  3005.5   252.6 3006.89   270.8  3010.3     289 3016.31
#Mann= 3 ,-1,0
       0      .1       0    79.6    .045       0    96.9      .1       0
#XS Ineff= 2 , 0
                          143.18         3000.48
Permanent Ineff=
       F       F
Bank Sta=79.6,96.9
XS Rating Curve= 0 ,0
Exp/Cntr(USF)=0,0
Exp/Cntr=0.3,0.1

Type RM Length L Ch R = 1 ,13460   ,125.1,127.3,130
XS GIS Cut Line= 4
2231326.47925889620330.9928752192231435.57221634620288.071055893
2231502.63755904620205.8042355182231541.08835552620178.978098439
#Sta/Elev= 30
       0 3014.73    10.4 3008.72    23.3 2998.88    31.9 2993.24    36.2 2990.91
    40.5 2989.51      49 2988.66    74.9 2989.53    96.4 2992.83   100.7 2991.28
     105 2988.02   109.3  2986.6   118.2  2986.5   125.4 2988.74   131.1 2989.21
   143.5 2981.61   148.1 2980.59   156.2 2979.93   167.4 2979.59   170.9 2979.94
   187.8 2983.22   193.2 2982.09   194.2 2982.28   198.4 2984.45     219 3004.49
   223.4  3007.4   239.3 3013.43   249.6 3016.09   259.3 3020.16   270.3 3022.98
#Mann= 3 ,-1,0
       0      .1       0   156.2    .045       0   170.9      .1       0
#XS Ineff= 2 , 0
                           187.8         2997.83
Permanent Ineff=
       F       F
Bank Sta=156.2,170.9
XS Rating Curve= 0 ,0
Exp/Cntr(USF)=0,0
Exp/Cntr=0.3,0.1