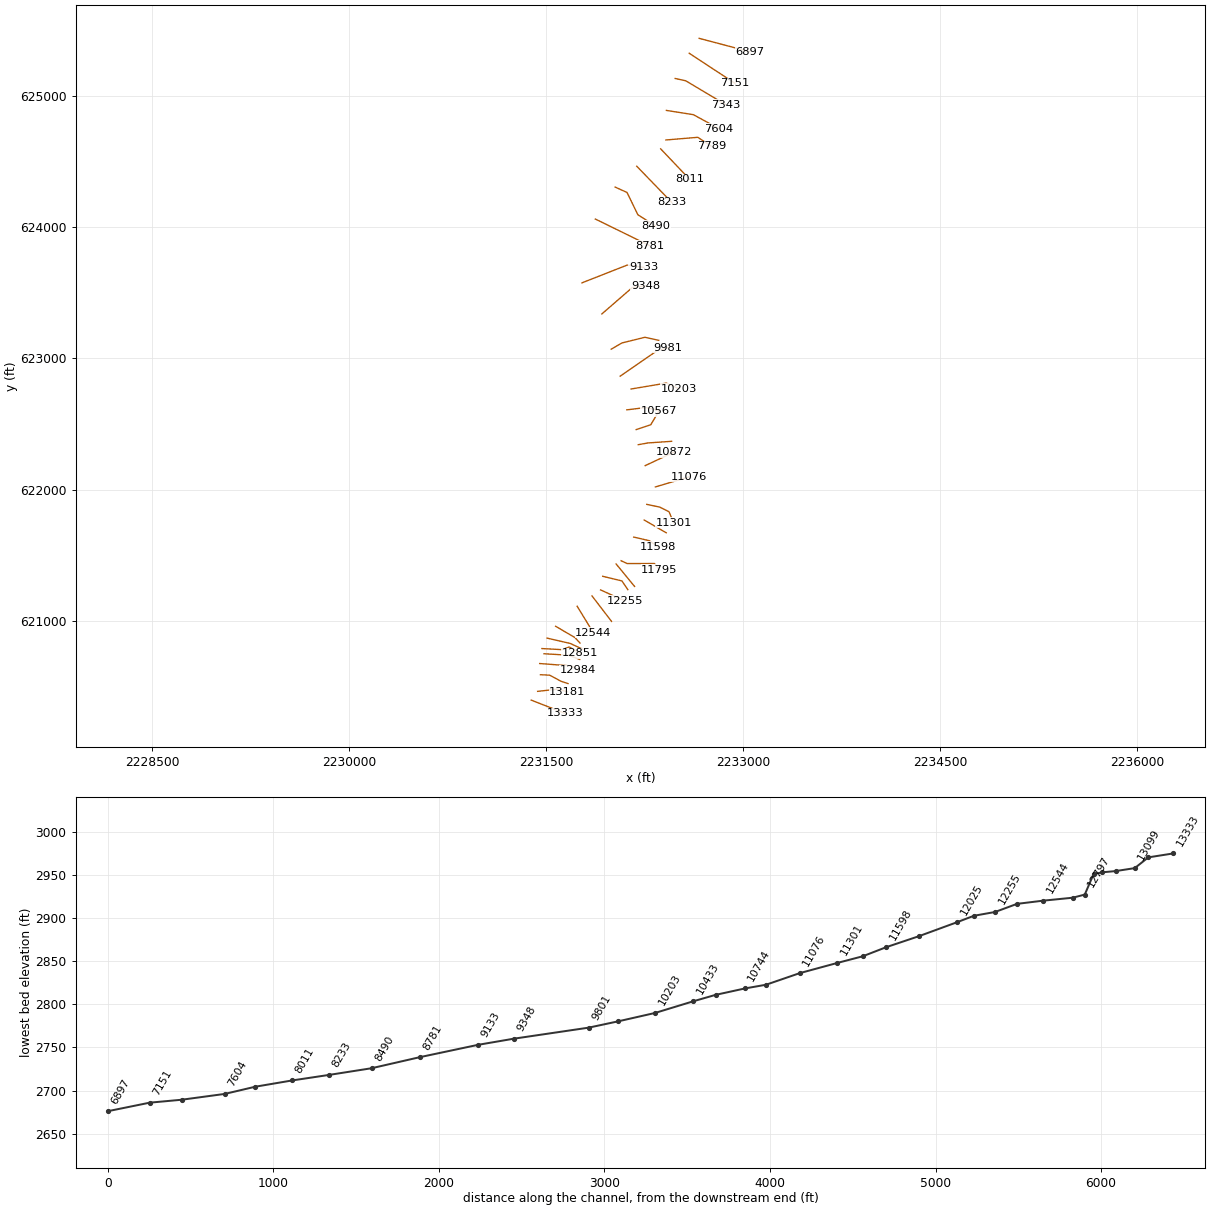
HEC-RAS study ROCKYRN.prj: ROCKYRN

--- ROCKYRN.g01 (geometry) --- (continued)

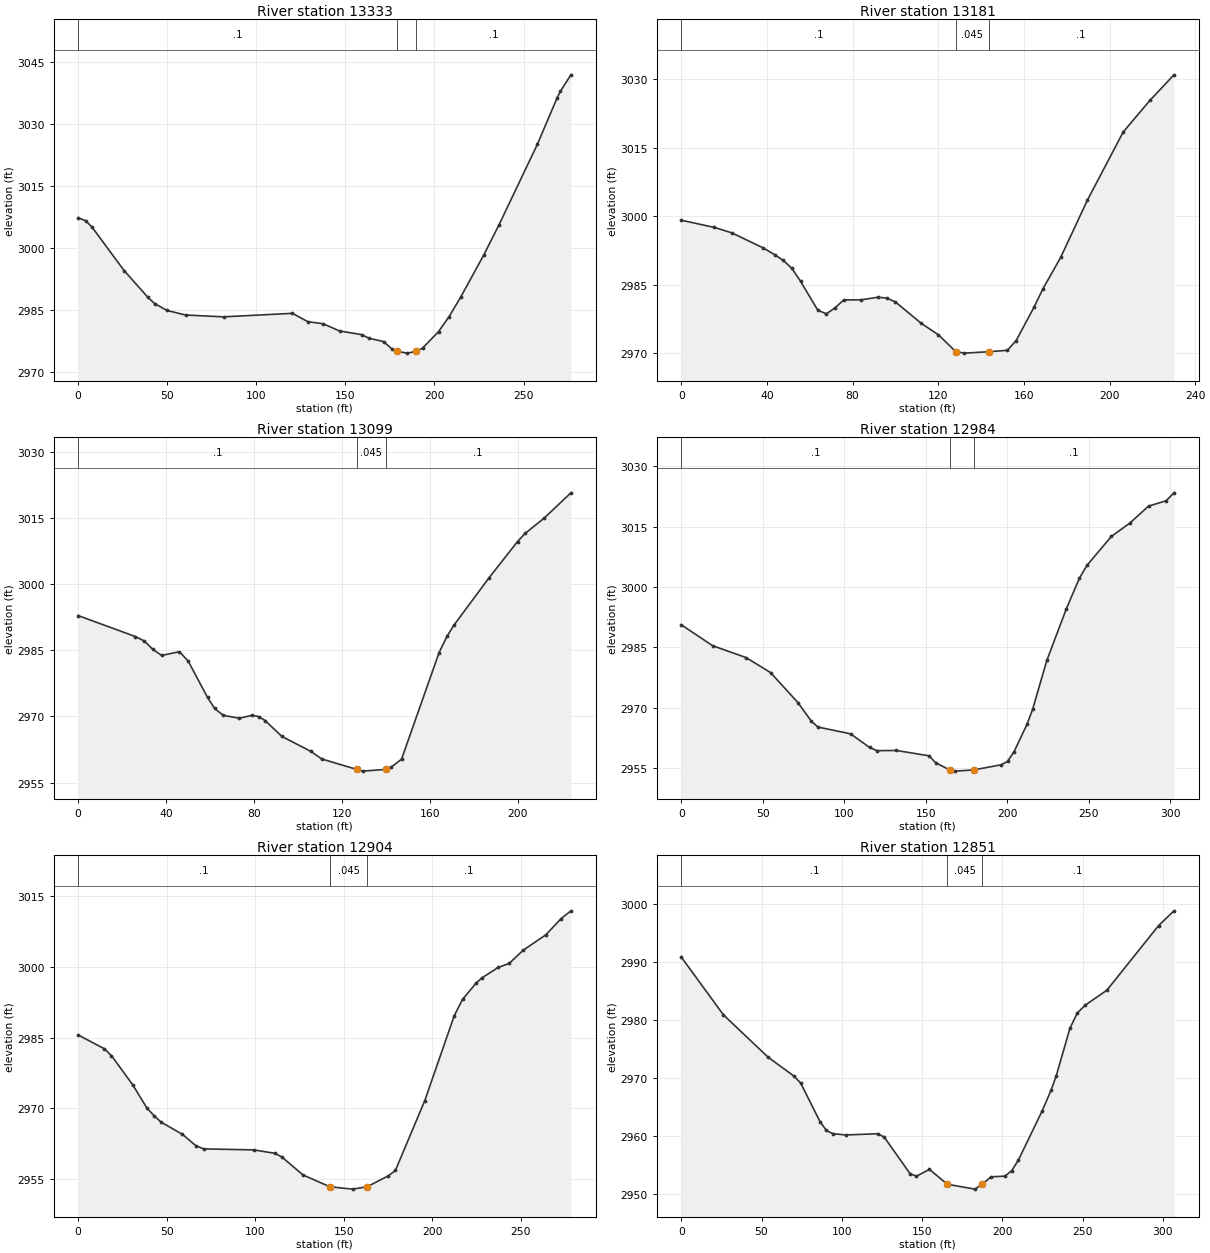
Type RM Length L Ch R = 1 ,13333   ,149.3,151.9,155.2
XS GIS Cut Line= 2
2231388.20290587620395.4085485872231645.73382183620294.363432257
#Sta/Elev= 30
       0 3007.39     4.3  3006.6     7.9 3005.04    25.8 2994.59      39  2988.2
    42.9 2986.63    49.9 2984.96    60.3 2983.86    81.6 2983.42   120.3 2984.27
   128.9 2982.25   137.5 2981.75   146.7 2980.01   159.1 2979.12   163.3 2978.24
   171.4 2977.45   176.1 2975.67  179.232975.076   184.7 2974.65   189.9 2975.08
   193.3 2975.86   202.3 2979.85   208.2 2983.46   214.8 2988.24   227.7 2998.39
   236.3 3005.71   257.8 3025.14   268.9 3036.38   270.7 3037.94   276.6 3041.91
#Mann= 3 ,-1,0
       0      .1       0  179.23    .045       0   189.9      .1       0
Bank Sta=179.23,189.9
XS Rating Curve= 0 ,0
Exp/Cntr(USF)=0,0
Exp/Cntr=0.3,0.1

Type RM Length L Ch R = 1 ,13181   ,85.5,82,77
XS GIS Cut Line= 3
2231436.76722645620462.1454805942231592.47465424620479.429220474
2231662.88094755620458.492951364
#Sta/Elev= 30
       0 2999.18    15.5 2997.59    23.6 2996.41    38.4 2993.08    43.7  2991.6
    47.7 2990.35    51.7 2988.61    55.7 2985.81    63.8 2979.44    67.8 2978.68
    71.8 2979.97    75.9 2981.72    83.9 2981.73      92 2982.31      96  2982.1
     100 2981.28   112.1 2976.58   120.1 2974.08   128.2 2970.38   132.2 2970.06
   143.5 2970.36   152.3 2970.68   156.4 2972.81   164.7 2980.07   168.9 2984.14
   177.2 2991.03   189.7 3003.59   206.4  3018.5   218.9 3025.43   230.1 3031.02
#Mann= 3 ,-1,0
       0      .1       0   128.2    .045       0   143.5      .1       0
Bank Sta=128.2,143.5
XS Rating Curve= 0 ,0
Exp/Cntr(USF)=0,0
Exp/Cntr=0.3,0.1

Type RM Length L Ch R = 1 ,13099   ,111.1,115.2,117.1
XS GIS Cut Line= 4
2231458.16735391620588.8249969252231528.65197969620585.500707752
2231616.15918228620538.5659937912231667.91950783620521.623170373
#Sta/Elev= 30
       0 2992.83      26 2988.09      30 2987.11      34 2985.18      38 2983.81
    46.1 2984.65    50.1 2982.51    58.9 2974.28    62.1 2971.79    66.1 2970.22
    73.4  2969.6    79.1 2970.23    82.3 2969.95    85.2 2969.02    92.7 2965.47
   105.9 2962.07   110.9 2960.35126.84752957.988   129.5  2957.6  139.922957.983
   142.6 2958.55   147.2  2960.3   164.3 2984.47   167.9 2988.14     171 2990.63
   186.8 3001.24     200  3009.6   203.5 3011.47     212 3014.85   224.3 3020.64
#Mann= 3 ,-1,0
       0      .1       0126.8475    .045       0  139.92      .1       0
Bank Sta=126.8475,139.92
XS Rating Curve= 0 ,0
Exp/Cntr(USF)=0,0
Exp/Cntr=0.3,0.1

Type RM Length L Ch R = 1 ,12984   ,79.3,79.5,80.3
XS GIS Cut Line= 3
2231452.55739682620674.325072769 2231697.5694488620655.546776814
2231744.06808641 620623.35541232
#Sta/Elev= 30
       0 2990.61    19.3 2985.39    39.7 2982.46    54.8 2978.72    71.8 2971.15
    79.9 2966.56    83.9 2965.16   103.9 2963.47   115.6 2960.07     120 2959.28
     132 2959.33   152.1    2958   156.1 2956.26   164.7  2954.5   168.1 2954.19
   179.6  2954.5   196.2 2955.76   200.2 2956.62   204.2 2959.03   212.2  2965.9
   215.6 2969.59   224.3 2981.73   236.3 2994.61   244.3 3002.21   248.9 3005.38
   263.9 3012.59   275.2  3015.9   286.7 3020.13   297.5 3021.47   302.3 3023.44
#Mann= 3 ,-1,0
       0      .1       0   164.7    .045       0   179.6      .1       0
Bank Sta=164.7,179.6
XS Rating Curve= 0 ,0
Exp/Cntr(USF)=0,0
Exp/Cntr=0.3,0.1

Type RM Length L Ch R = 1 ,12904   ,45,53.6,54
XS GIS Cut Line= 3
2231485.39562399620748.7275992742231672.08837314620737.696967349
2231757.40357635620705.494547244
#Sta/Elev= 30
       0 2985.53    14.8 2982.61    18.8 2981.15    30.8 2974.94    38.8 2970.02
    42.9 2968.36    46.9    2967    58.9 2964.42    66.5 2961.99    70.9 2961.33
      99 2961.12     111  2960.4     115 2959.61   126.9  2955.8   142.2 2953.27
     155 2952.78   163.1 2953.28   175.1  2955.6   179.1 2956.74   195.7 2971.59
   212.3  2989.6     217  2993.1   224.7 2996.57   227.8 2997.63   237.1 2999.88
   243.4 3000.76   251.2 3003.53   264.1 3006.84   272.6 3010.24   278.2 3011.92
#Mann= 3 ,-1,0
       0      .1       0   142.2    .045       0   163.1      .1       0
Bank Sta=142.2,163.1
XS Rating Curve= 0 ,0
Exp/Cntr(USF)=0,0
Exp/Cntr=0.3,0.1

Type RM Length L Ch R = 1 ,12851   ,58.1,53.4,50
XS GIS Cut Line= 4
2231469.92784506620788.3361159872231622.20163306620780.047047711
2231677.79226588620800.5524802922231760.57570059  620753.5782224
#Sta/Elev= 30
       0 2990.89    26.3 2980.89    54.1 2973.58    70.4 2970.27    74.4  2969.1
    86.4 2962.46    90.4 2960.91    94.4 2960.36   102.4 2960.13   122.4 2960.35
   126.4 2959.77   142.5 2953.45   146.5    2953   154.6 2954.18  165.76 2951.61
   182.9 2950.77   187.42951.624     193  2952.9   201.5 2953.01   205.8 2953.94
     210 2955.79   224.8 2964.29   230.4  2967.9   233.6 2970.37   242.1 2978.57
   246.7 2981.22   251.6 2982.57   265.1 2985.15   297.3 2996.32   306.9 2998.88
#Mann= 3 ,-1,0
       0      .1       0  165.76    .045       0   187.4      .1       0
Bank Sta=165.76,187.4
XS Rating Curve= 0 ,0
Exp/Cntr(USF)=0,0
Exp/Cntr=0.3,0.1

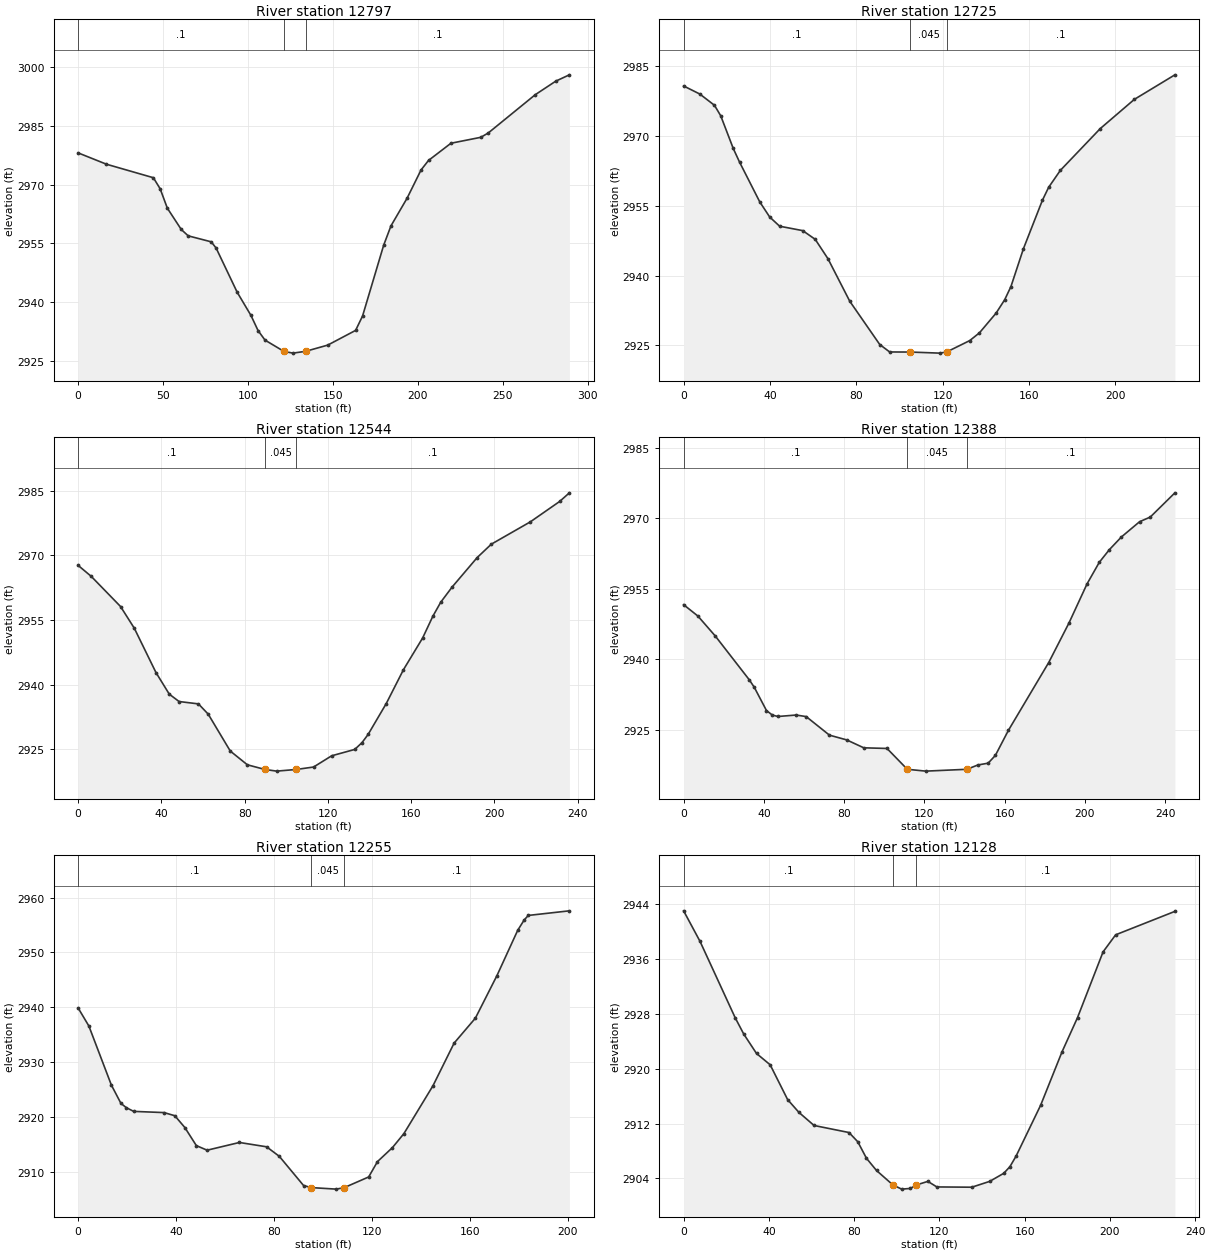
Type RM Length L Ch R = 1 ,12797   ,74.9,72.8,71.3
XS GIS Cut Line= 3
2231508.98598955620867.8178587462231684.25008514620827.578653128
2231783.50679233620781.974220094
#Sta/Elev= 30
       0 2978.13    16.7 2975.23    44.3 2971.78    48.3 2968.94    52.5 2964.01
    60.7 2958.56    64.8 2956.93    78.3 2955.41    81.2 2953.83    93.6 2942.53
   101.7 2936.61   105.9 2932.73     110 2930.29   121.12927.419   126.4 2926.97
   133.9 2927.43   146.9 2929.02   163.3 2932.78   167.4 2936.47   179.8 2954.53
   184.1 2959.48   193.6 2966.56   201.8 2973.76   206.2  2976.2   219.4 2980.59
     237 2982.11   241.4 2983.23     269 2992.99   281.1 2996.46   289.1 2998.07
#Mann= 3 ,-1,0
       0      .1       0   121.1    .045       0   133.9      .1       0
Bank Sta=121.1,133.9
XS Rating Curve= 0 ,0
Exp/Cntr(USF)=0,0
Exp/Cntr=0.3,0.1

Type RM Length L Ch R = 1 ,12725   ,182.8,180.5,174.5
XS GIS Cut Line= 3
2231573.73354853620958.2510728892231720.86511245620872.209222644
2231759.58394506620830.048716024
#Sta/Elev= 30
       0  2980.7     7.5 2978.97    14.3 2976.55    17.2  2974.3      23 2967.29
    25.9 2964.38    35.3 2955.81    39.9 2952.57    44.5  2950.6    55.2 2949.65
      61 2947.78    66.9 2943.62      77  2934.5    90.9 2925.21    95.5 2923.61
   105.1 2923.59   118.7 2923.36  121.892923.602   132.6 2926.05   137.1 2927.71
   144.8 2931.93   148.8 2934.81   151.7 2937.64   157.5 2945.78   166.3 2956.18
   169.2 2958.96   174.6 2962.58   193.1 2971.55   208.9 2977.82   227.7 2983.09
#Mann= 3 ,-1,0
       0      .1       0   105.1    .045       0  121.89      .1       0
Bank Sta=105.1,121.89
XS Rating Curve= 0 ,0
Exp/Cntr(USF)=0,0
Exp/Cntr=0.3,0.1

Type RM Length L Ch R = 1 ,12544   ,152.9,155.8,159.4
XS GIS Cut Line= 2
 2231738.0734825621110.5451478212231861.11332835620909.207218249
#Sta/Elev= 30
       0 2967.66     6.3 2965.11    20.4  2958.1      27 2953.06    37.4 2942.78
    43.8 2937.76    48.5 2936.05    57.8  2935.5    62.5 2933.12    73.1 2924.55
    81.3 2921.36    89.8 2920.27    95.4 2919.89   104.7 2920.27   113.1 2920.84
   121.8 2923.45   132.9 2924.93   136.4 2926.52   139.3  2928.4     148 2935.56
   156.3 2943.45   165.5  2950.8   170.4 2955.84   174.2 2959.11   179.7 2962.65
   191.7 2969.47   198.5 2972.58   217.2 2977.75   231.3 2982.49     236  2984.5
#Mann= 3 ,-1,0
       0      .1       0    89.8    .045       0   104.7      .1       0
Bank Sta=89.8,104.7
XS Rating Curve= 0 ,0
Exp/Cntr(USF)=0,0
Exp/Cntr=0.3,0.1

Type RM Length L Ch R = 1 ,12388   ,128.1,132.9,139.1
XS GIS Cut Line= 2
2231850.78830632621189.7036500462231999.64070724620995.249068494
#Sta/Elev= 30
       0 2951.64     7.1 2949.23    15.8 2944.97    32.7 2935.68    35.2 2934.09
    41.3 2929.13    44.2 2928.17      47 2927.86    56.1 2928.17    61.1 2927.84
    72.7 2923.89    81.3 2922.88    89.8  2921.2   101.4 2921.06   111.5 2916.63
   120.7 2916.24   141.2 2916.63   146.7 2917.55   151.8 2917.93   155.4 2919.58
   161.9 2924.91     182 2939.34   192.1 2947.75   201.1 2956.06   207.2 2960.65
   212.2 2963.33   218.2 2966.03   227.3 2969.29   232.6 2970.27   244.9 2975.43
#Mann= 3 ,-1,0
       0      .1       0   111.5    .045       0   141.2      .1       0
Bank Sta=111.5,141.2
XS Rating Curve= 0 ,0
Exp/Cntr(USF)=0,0
Exp/Cntr=0.3,0.1

Type RM Length L Ch R = 1 ,12255   ,125.6,127.8,128.4
XS GIS Cut Line= 3
2231916.20635752621235.2781688962232046.83249979621175.722743586
 2232099.7613602621154.188869533
#Sta/Elev= 30
       0 2939.87     4.4 2936.57    13.6 2925.79    17.5 2922.46    19.7 2921.68
    22.7    2921    35.1 2920.78    39.5 2920.21    43.6 2918.06    48.3 2914.76
    52.7 2913.92    65.9 2915.33      77 2914.54    82.2  2912.8    92.1 2907.48
    95.2  2907.1   105.5 2906.82   108.8 2907.11   118.7 2909.04   122.3 2911.84
   128.4 2914.39   133.1 2916.95     145  2925.7   153.6 2933.45   162.3 2938.01
   171.1 2945.76   179.6 2954.04   182.2 2955.89   183.9 2956.74   200.7 2957.58
#Mann= 3 ,-1,0
       0      .1       0    95.2    .045       0   108.8      .1       0
Bank Sta=95.2,108.8
XS Rating Curve= 0 ,0
Exp/Cntr(USF)=0,0
Exp/Cntr=0.3,0.1

Type RM Length L Ch R = 1 ,12128   ,101.6,102.2,94.6
XS GIS Cut Line= 3
2231932.72412404621338.9738585382232078.74415338621303.772601463
2232123.72353742621237.281338099
#Sta/Elev= 30
       0 2943.05     7.7 2938.59    24.2 2927.44    28.2 2925.07    34.2 2922.23
    40.6 2920.58    48.8  2915.5    54.1 2913.63    61.2 2911.72    77.6 2910.69
    81.7 2909.35    85.8 2906.93    90.5 2905.15    98.2 2903.04   102.3 2902.43
   106.4 2902.53  109.242903.041   114.6 2903.56   118.8 2902.75   135.2 2902.71
   143.6 2903.56   150.2 2904.74   153.1 2905.71     156 2907.26   167.5 2914.67
   177.5 2922.44   184.8 2927.46   196.8 2937.06   202.7 2939.55   230.5 2942.97
#Mann= 3 ,-1,0
       0      .1       0    98.2    .045       0  109.24      .1       0
Bank Sta=98.2,109.24
XS Rating Curve= 0 ,0
Exp/Cntr(USF)=0,0
Exp/Cntr=0.3,0.1

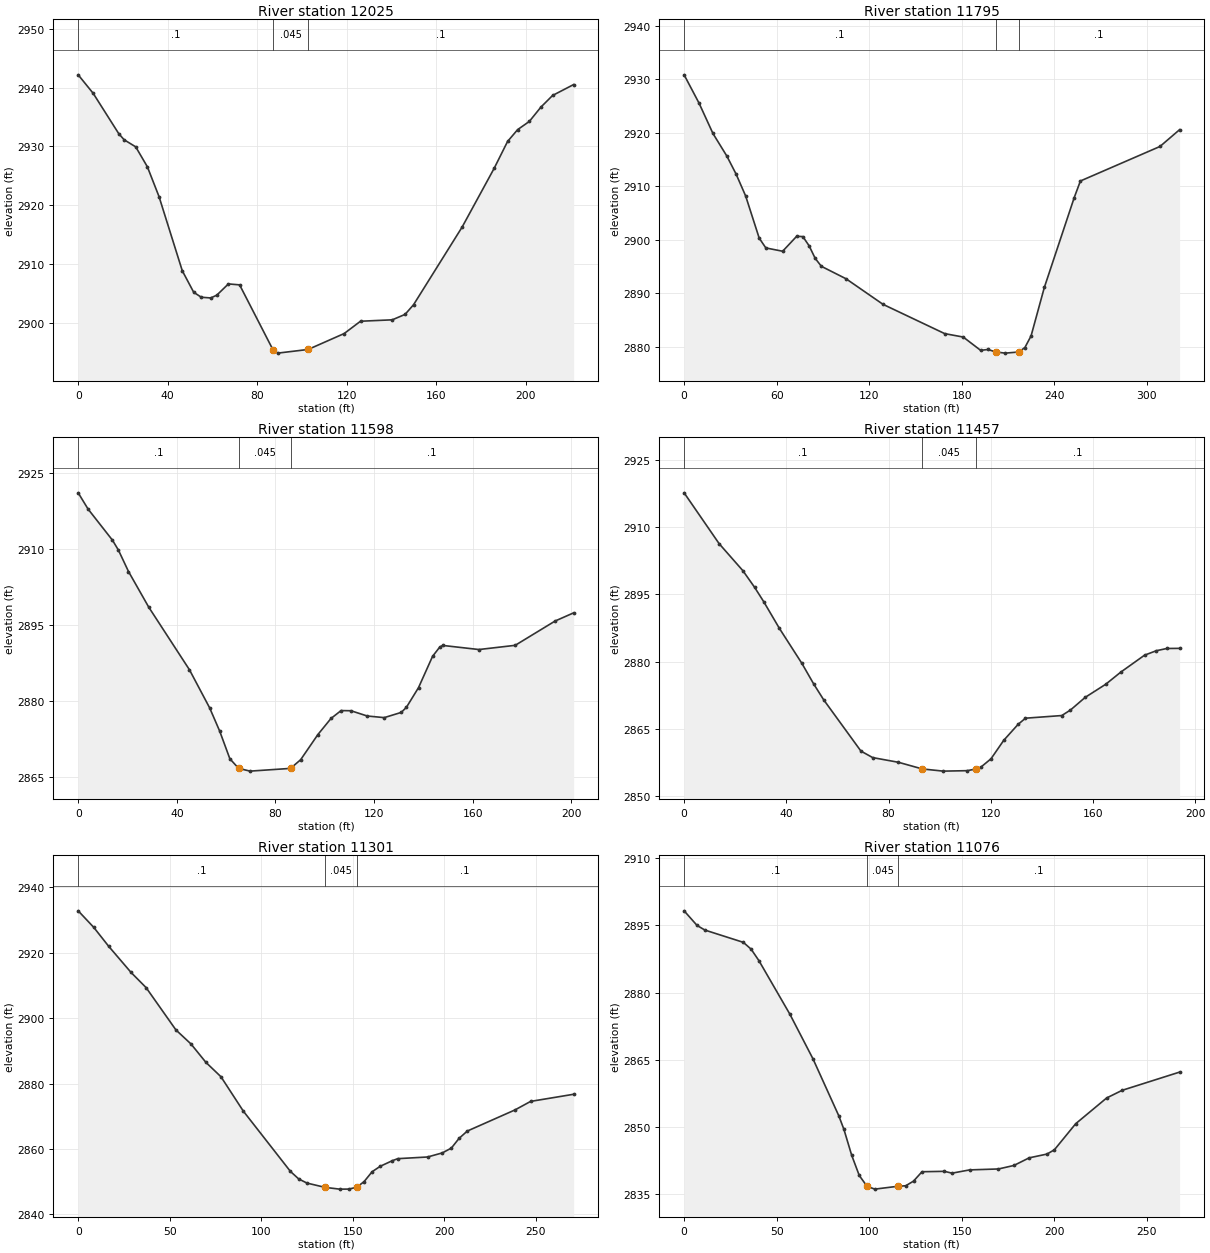
Type RM Length L Ch R = 1 ,12025   ,225.5,230.3,238
XS GIS Cut Line= 2
 2232034.6582492621433.072277916 2232174.9064651 621261.84899593
#Sta/Elev= 30
       0 2942.15     6.7 2939.01    18.1 2932.18    20.5 2931.14    25.7 2929.93
    30.9 2926.55    36.1  2921.5    46.5 2908.91    51.6 2905.26      55 2904.42
    59.2  2904.3    61.9 2904.77    67.1 2906.68    72.1 2906.52   86.962895.539
    89.1 2894.94   102.7 2895.56   118.8 2898.26   126.1 2900.35   140.3 2900.59
     146 2901.51   149.8 2903.15   171.5 2916.33   185.8 2926.29   191.8 2930.85
   196.3 2932.86   201.5 2934.24   206.7 2936.68   211.9 2938.65   221.3  2940.5
#Mann= 3 ,-1,0
       0      .1       0   86.96    .045       0   102.7      .1       0
Bank Sta=86.96,102.7
XS Rating Curve= 0 ,0
Exp/Cntr(USF)=0,0
Exp/Cntr=0.3,0.1

Type RM Length L Ch R = 1 ,11795   ,197.9,197,191.3
XS GIS Cut Line= 4
2232072.09532628  621457.94709622232118.50853637621436.103253059
2232326.59973817621436.6437602472232364.45815228621387.599905608
#Sta/Elev= 30
       0 2930.85     9.7 2925.54    18.7 2919.87    27.7 2915.65    33.7 2912.28
    39.9 2908.18    48.7 2900.28      53 2898.45    63.9 2897.83      73 2900.63
      77 2900.57      81 2898.88      85  2896.5      89 2895.01     105 2892.68
     129 2887.89     169 2882.41     181 2881.77   192.3 2879.28     197 2879.44
   202.32878.966   208.3 2878.76     217 2878.97     221 2879.81     225 2881.98
   233.6 2891.05     253 2907.88     257 2910.98   308.6 2917.44   321.3 2920.58
#Mann= 3 ,-1,0
       0      .1       0   202.3    .045       0     217      .1       0
Bank Sta=202.3,217
XS Rating Curve= 0 ,0
Exp/Cntr(USF)=0,0
Exp/Cntr=0.3,0.1

Type RM Length L Ch R = 1 ,11598   ,140.3,141.3,133.8
XS GIS Cut Line= 3
2232168.28273372621637.9816898192232287.02048706621610.448297741
2232351.55187474621564.846117111
#Sta/Elev= 30
       0    2921       4  2917.8    13.9 2911.65    16.3 2909.71    20.4 2905.47
    28.6 2898.44    45.1 2886.09    53.3 2878.56    57.4 2873.94    61.5 2868.51
   65.07 2866.61    69.7 2866.07    86.1 2866.61    90.2 2868.32    97.2 2873.29
   102.5 2876.46   106.6 2878.02   110.6 2877.99   117.2 2876.95   124.1 2876.63
     131 2877.66   133.1 2878.67     138 2882.55   143.7 2888.73   146.6 2890.55
   147.8 2890.88   162.5 2890.07   177.2  2890.9   193.4  2895.7   200.9 2897.31
#Mann= 3 ,-1,0
       0      .1       0   65.07    .045       0    86.1      .1       0
Bank Sta=65.07,86.1
XS Rating Curve= 0 ,0
Exp/Cntr(USF)=0,0
Exp/Cntr=0.3,0.1

Type RM Length L Ch R = 1 ,11457   ,154.1,156,156.4
XS GIS Cut Line= 2
2232248.30165445621767.9048836882232416.08326242621670.677592912
#Sta/Elev= 30
       0 2917.65    13.7 2906.31      23 2900.28    27.6 2896.56    31.2 2893.32
    37.3  2887.4    46.1 2879.59    50.7 2875.02    54.6 2871.49    69.2 2860.03
    73.8 2858.58    83.9 2857.53    93.2 2856.05   101.4 2855.56   110.8 2855.66
  114.25 2856.05   116.1 2856.43   120.1 2858.31   125.1 2862.44   130.7 2865.99
   133.6 2867.37   147.8 2867.96   151.2 2869.19     157 2872.03     165 2874.94
   170.9 2877.65   180.2 2881.43   184.8 2882.42   188.9 2882.92   193.9 2882.95
#Mann= 3 ,-1,0
       0      .1       0    93.2    .045       0  114.25      .1       0
Bank Sta=93.2,114.25
XS Rating Curve= 0 ,0
Exp/Cntr(USF)=0,0
Exp/Cntr=0.3,0.1

Type RM Length L Ch R = 1 ,11301   ,217,224.9,229.4
XS GIS Cut Line= 4
2232267.89684614621887.2820779622232366.72203052621866.283972401
2232437.35463285621831.3973724972232472.33544247621747.519205246
#Sta/Elev= 30
       0 2932.78     8.5 2927.73    16.6 2921.98    28.9 2913.94    37.1 2909.32
    53.4 2896.38    61.6 2892.11    69.8 2886.46      78 2882.08    90.2 2871.59
     116 2853.12   120.5 2850.84     125 2849.58  134.85 2848.27   142.8 2847.73
   147.7 2847.74   152.12848.272   156.2 2850.02   160.6 2853.05   165.1 2854.73
   171.6 2856.41   174.6 2857.04   190.9 2857.55     199 2858.81   203.9 2860.28
   208.1 2863.24   212.6 2865.48   238.6 2871.92   247.2 2874.54   270.7 2876.72
#Mann= 3 ,-1,0
       0      .1       0  134.85    .045       0   152.1      .1       0
Bank Sta=134.85,152.1
XS Rating Curve= 0 ,0
Exp/Cntr(USF)=0,0
Exp/Cntr=0.3,0.1

Type RM Length L Ch R = 1 ,11076   ,201.4,203.6,204
XS GIS Cut Line= 2
2232333.48308619622020.0075049042232589.88779992622096.507433333
#Sta/Elev= 30
       0 2898.27       7    2895    11.2 2893.97      32 2891.22    36.2 2889.69
    40.4 2887.13    57.1 2875.17    69.6 2865.17    83.5 2852.47    86.3 2849.41
    90.5 2843.61    94.6 2839.08    98.8 2836.66     103 2836.03   115.5 2836.67
   119.7 2836.78   123.9 2837.82   128.5 2839.92   140.6 2840.01   144.7  2839.6
   154.2 2840.33   169.8 2840.54   178.1 2841.32   186.4 2843.03     196 2843.87
     200 2844.83   211.5 2850.66   228.2 2856.41   236.6 2858.13   267.6  2862.2
#Mann= 3 ,-1,0
       0      .1       0    98.8    .045       0   115.5      .1       0
Bank Sta=98.8,115.5
XS Rating Curve= 0 ,0
Exp/Cntr(USF)=0,0
Exp/Cntr=0.3,0.1

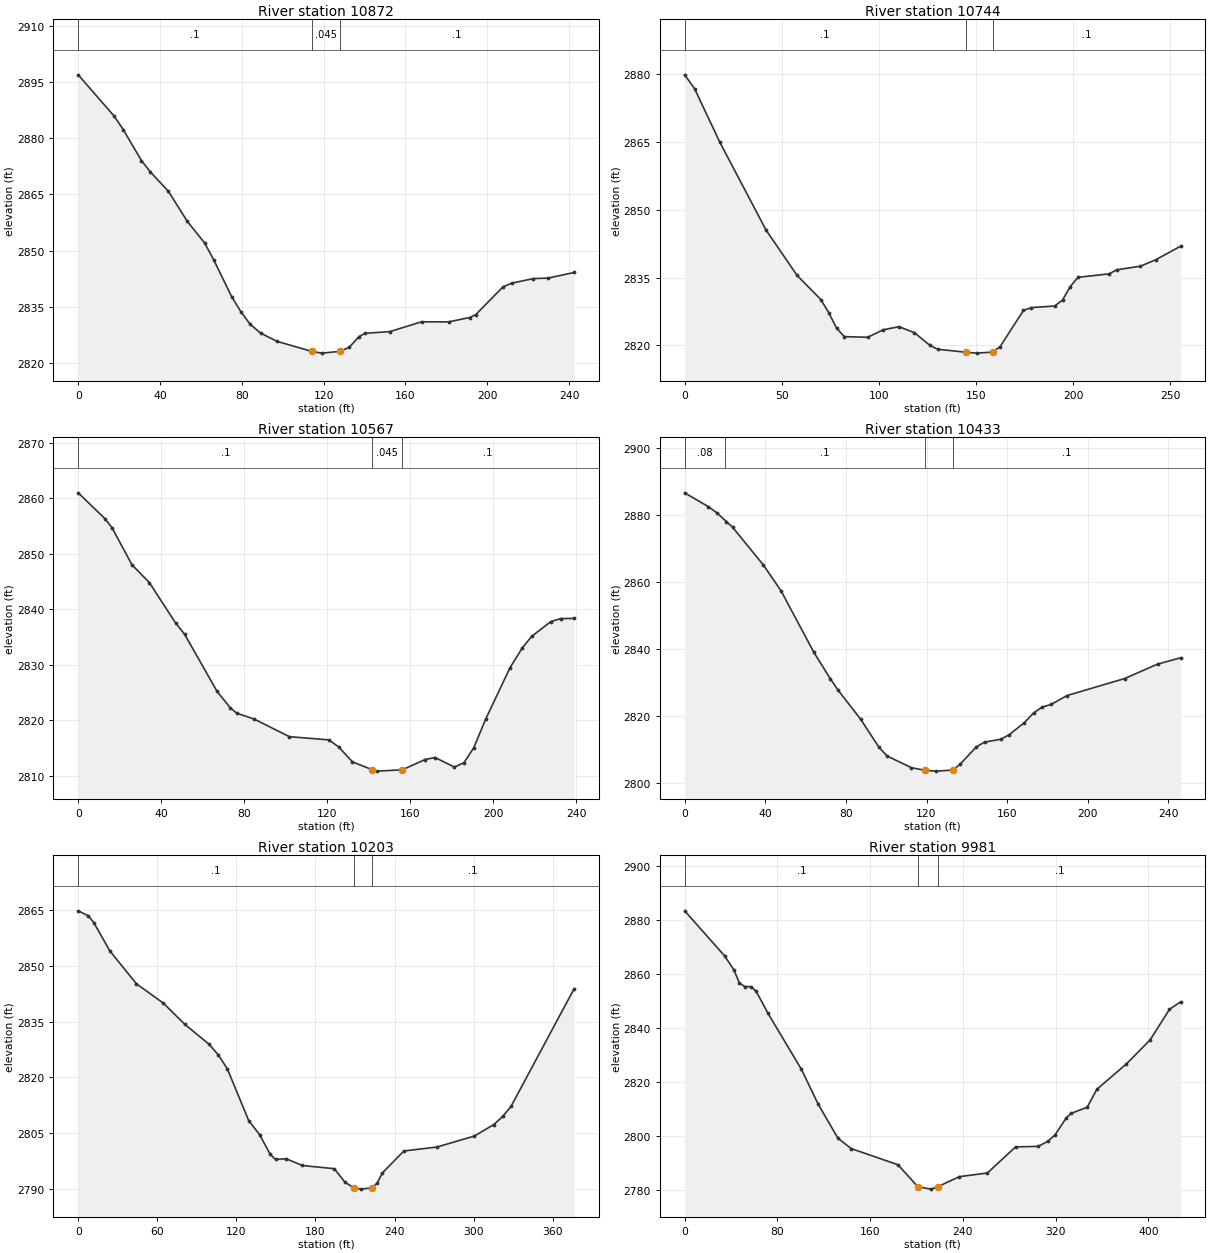
Type RM Length L Ch R = 1 ,10872   ,131.2,128.1,126.2
XS GIS Cut Line= 2
2232256.23782175622182.4656200512232475.64453987622285.715840344
#Sta/Elev= 30
       0 2896.98    17.6 2885.93      22 2882.36    30.9 2874.08    35.3    2871
    44.1 2865.86    53.3 2857.85    61.8 2852.06    66.2 2847.59    75.1 2837.62
    79.5 2833.71    83.9 2830.43    89.2 2827.94    97.2 2825.75  114.292823.048
   119.1  2822.6   128.1 2823.07   132.6 2824.21   137.3    2827   140.3 2827.91
   152.3 2828.34   167.9 2830.97   181.2 2830.96   191.4 2832.12   194.4 2832.91
   207.7 2840.31   212.1 2841.31   222.4 2842.51   229.8 2842.66   242.5 2844.16
#Mann= 3 ,-1,0
       0      .1       0  114.29    .045       0   128.1      .1       0
Bank Sta=114.29,128.1
XS Rating Curve= 0 ,0
Exp/Cntr(USF)=0,0
Exp/Cntr=0.3,0.1

Type RM Length L Ch R = 1 ,10744   ,172.4,176.9,185.9
XS GIS Cut Line= 3
2232203.17164927  622341.99298412232276.83535237622355.228108256
2232456.82724268622367.777561705
#Sta/Elev= 30
       0 2879.85     5.1 2876.78      18 2865.02    41.9  2845.5    57.9 2835.46
    70.1 2830.13    74.2  2827.2    78.2 2823.79    82.2 2821.93    94.2 2821.79
   102.2 2823.44   110.3 2824.13   118.3  2822.8   126.3 2819.97   130.3 2819.14
  144.682818.478   150.4 2818.28   158.5 2818.51   162.4 2819.73   174.4 2827.73
   178.4 2828.35   190.5  2828.7   194.5 2830.02   198.5 2833.02   202.5 2835.06
   218.5 2835.81   222.5 2836.73   234.6 2837.51   242.6 2838.95   255.3 2841.95
#Mann= 3 ,-1,0
       0      .1       0  144.68    .045       0   158.5      .1       0
Bank Sta=144.68,158.5
XS Rating Curve= 0 ,0
Exp/Cntr(USF)=0,0
Exp/Cntr=0.3,0.1

Type RM Length L Ch R = 1 ,10567   ,139,134.7,126.2
XS GIS Cut Line= 3
2232187.62468773 622457.108104532232298.67418398622493.976537283
2232360.86190187622598.807261738
#Sta/Elev= 30
       0 2860.99    12.9 2856.33    16.3 2854.69    25.9 2848.02    34.3 2844.81
    46.9 2837.54    51.2 2835.54    66.9 2825.21    73.3 2822.24    76.4 2821.28
    84.9 2820.21   101.7 2817.06   120.7 2816.48   125.4 2815.23   132.1 2812.52
  141.682811.097     144 2810.85   156.12811.088   167.1 2812.94   171.9  2813.3
   181.2 2811.58   185.8 2812.36   190.5 2815.04   196.3 2820.24     208 2829.48
     214 2833.09   218.4 2835.12   227.7  2837.8   232.4 2838.33   238.9 2838.36
#Mann= 3 ,-1,0
       0      .1       0  141.68    .045       0   156.1      .1       0
Bank Sta=141.68,156.1
XS Rating Curve= 0 ,0
Exp/Cntr(USF)=0,0
Exp/Cntr=0.3,0.1

Type RM Length L Ch R = 1 ,10433   ,227.8,230,228.7
XS GIS Cut Line= 3
2232116.53539922622607.5607261542232260.04971281622625.224026288
2232359.40577606622604.248857379
#Sta/Elev= 30
       0 2886.63    11.7 2882.51    15.8 2880.74    20.7 2878.05    23.8 2876.33
    39.1 2865.01    47.8 2857.35    64.1 2838.95    72.2  2831.1    76.2 2827.58
    87.3 2818.96    96.4 2810.56   100.4 2807.97   112.5 2804.44   119.5 2803.64
   124.6 2803.42  132.942803.719   136.7 2805.49   144.7 2810.66   148.8  2812.1
     157 2812.96   161.1 2814.34   168.4 2817.84   173.3 2820.88   177.4 2822.57
   181.9 2823.38   189.7 2826.01   218.3  2831.1   234.7 2835.42   246.1  2837.3
#Mann= 4 ,-1,0
       0     .08       0      20      .1       0   119.5    .045       0
  132.94      .1       0
Bank Sta=119.5,132.94
XS Rating Curve= 0 ,0
Exp/Cntr(USF)=0,0
Exp/Cntr=0.3,0.1

Type RM Length L Ch R = 1 ,10203   ,218.1,221.3,224.1
XS GIS Cut Line= 3
2232148.55013071622766.337378726 2232416.8115015 622811.59958532
2232511.75173972622768.545291242
#Sta/Elev= 30
       0 2864.86     7.7  2863.5    11.8 2861.71      24 2854.07    44.2 2845.21
    64.5 2840.04    80.8 2834.33    99.3 2828.95   106.3 2826.09   113.2 2822.29
   129.4 2808.37   137.6 2804.64   145.7  2799.3   149.7 2797.95   157.8 2798.13
     170 2796.31   194.3 2795.45   202.4  2791.8   209.2  2790.3   214.6 2789.95
   223.12790.308   226.8 2791.57   230.8 2794.32   247.1 2800.22   272.1 2801.27
   300.6 2804.24   315.3 2807.32   322.2 2809.54   328.5 2812.28   376.3 2843.91
#Mann= 3 ,-1,0
       0      .1       0   209.2    .045       0   223.1      .1       0
Bank Sta=209.2,223.1
XS Rating Curve= 0 ,0
Exp/Cntr(USF)=0,0
Exp/Cntr=0.3,0.1

Type RM Length L Ch R = 1 ,9981    ,183.1,179.8,176.8
XS GIS Cut Line= 3
2232065.31450943622864.0780636632232343.43992281623056.405722682
2232429.38838705623082.390142103
#Sta/Elev= 30
       0 2883.32    34.5 2866.62    42.4 2861.51    47.2 2856.62    51.7 2855.31
    57.5 2855.23    61.8 2853.46    71.8 2845.42   100.6 2824.75   115.3 2811.67
   132.2 2799.17   143.7 2795.31     184 2789.34   201.2  2781.2   212.6 2780.31
   218.5 2781.23   236.9 2784.91   261.2 2786.29   285.5 2795.95     305 2796.13
   313.4 2798.02   319.6 2800.41   329.3 2806.73   333.5 2808.36   347.3 2810.62
   355.6 2817.25   381.1 2826.64   401.6 2835.55   418.3 2846.86   427.9 2849.64
#Mann= 3 ,-1,0
       0      .1       0   201.2    .045       0   218.5      .1       0
Bank Sta=201.2,218.5
XS Rating Curve= 0 ,0
Exp/Cntr(USF)=0,0
Exp/Cntr=0.3,0.1

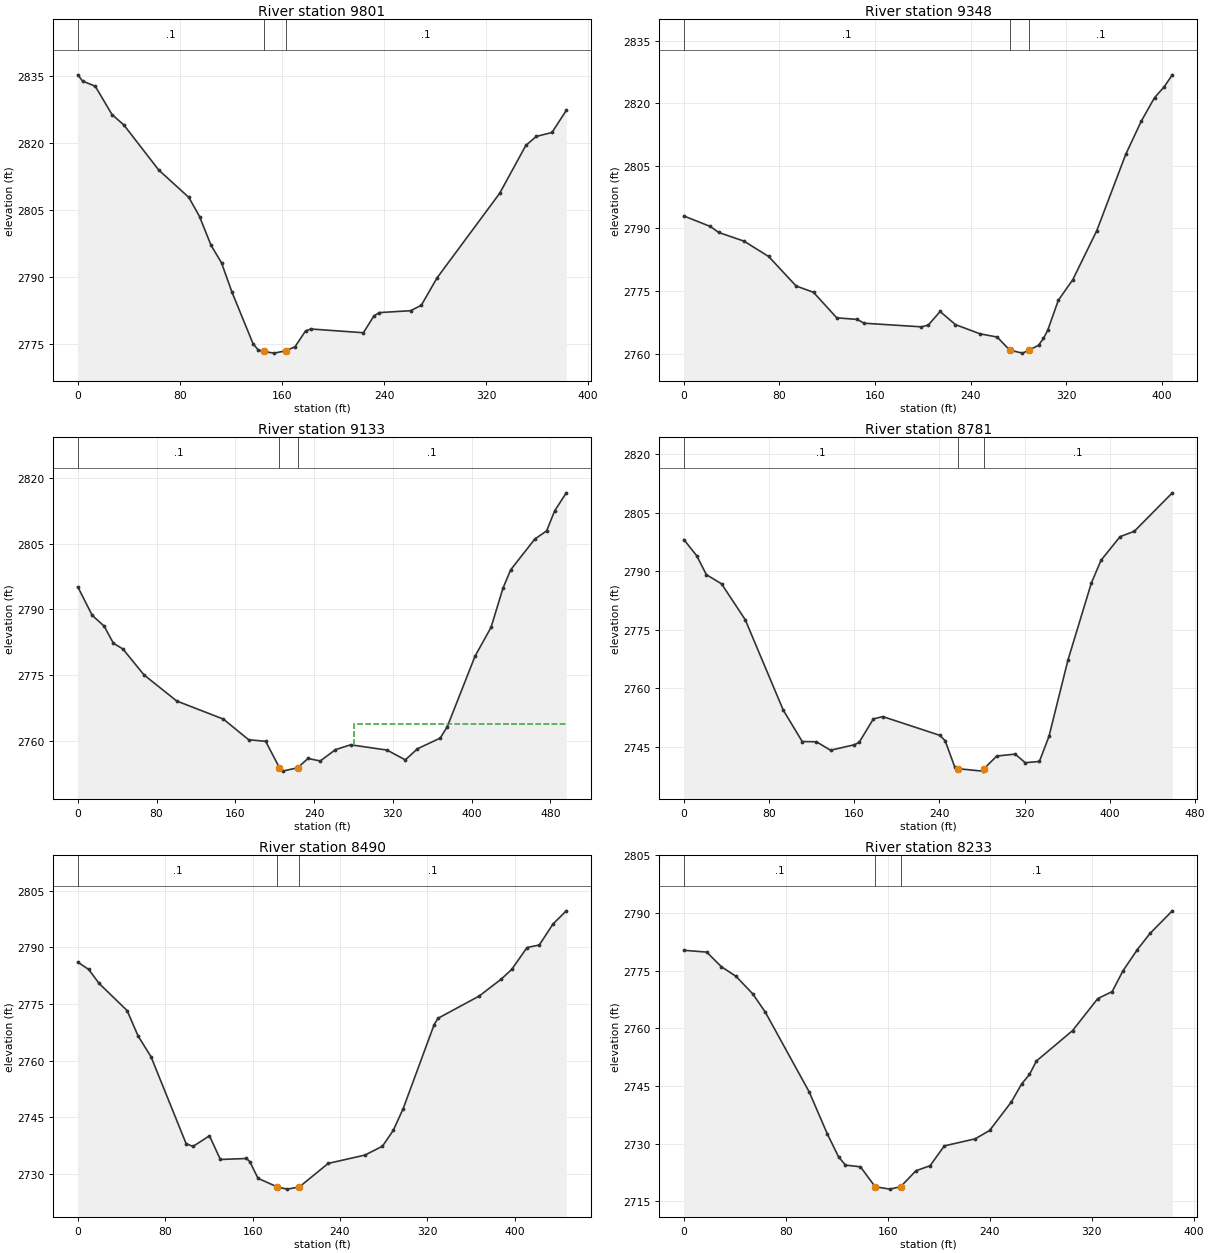
Type RM Length L Ch R = 1 ,9801    ,447.7,452.9,454.8
XS GIS Cut Line= 4
2231996.94835747623069.6997873892232079.44550887623117.527718883
 2232253.8705977 623160.582012962232359.16472944623137.357618426
#Sta/Elev= 30
       0 2835.29     3.7  2833.9    13.7 2832.72    26.8 2826.38    36.1 2824.05
    63.4 2813.96      87 2807.82    95.4 2803.53   104.4  2797.1   112.6 2793.17
   120.8 2786.59   137.3 2775.06   141.4 2773.63   145.72773.297   153.8 2772.93
   163.32773.468   170.3 2774.38   178.5 2777.92   182.6 2778.34   223.8  2777.5
   232.1 2781.28   236.2 2782.01   260.9 2782.44   269.2 2783.66   281.5 2789.78
   330.6 2808.74   351.1 2819.46   359.3 2821.49   371.6 2822.37   382.8 2827.32
#Mann= 3 ,-1,0
       0      .1       0   145.7    .045       0   163.3      .1       0
Bank Sta=145.7,163.3
XS Rating Curve= 0 ,0
Exp/Cntr(USF)=0,0
Exp/Cntr=0.3,0.1

Type RM Length L Ch R = 1 ,9348    ,216.4,215.8,209.3
XS GIS Cut Line= 3
 2231926.2103554623338.6794489282232158.51404429623540.256980059
2232258.95523573623552.249789023
#Sta/Elev= 30
       0 2792.99    22.1 2790.48    29.1 2789.05    50.3 2786.96    70.9 2783.29
    93.9 2776.22   108.5 2774.69   127.9 2768.58   144.9  2768.2   150.9 2767.29
   198.8 2766.42   204.5 2766.84   214.4  2770.1   227.2 2766.96   247.9 2764.74
   262.1 2763.98   272.7 2760.83   283.3 2760.12   288.6  2760.8   296.8 2762.01
   300.9 2763.64   304.5 2765.64   313.3 2772.78   325.4 2777.71   345.5 2789.48
   369.7 2807.74   382.8 2815.76   393.8 2821.33   401.9 2823.95   408.7 2826.82
#Mann= 3 ,-1,0
       0      .1       0   272.7    .045       0   288.6      .1       0
Bank Sta=272.7,288.6
XS Rating Curve= 0 ,0
Exp/Cntr(USF)=0,0
Exp/Cntr=0.3,0.1

Type RM Length L Ch R = 1 ,9133    ,355.4,352.5,340.2
XS GIS Cut Line= 3
2231774.60286161623575.423456413  2232119.392737623711.037672176
2232243.85738624623693.613541718
#Sta/Elev= 30
       0 2795.09    14.6  2788.6    26.7 2786.15    36.1 2782.24    45.8 2780.91
    67.3 2774.98   100.5 2769.03   147.8 2764.91   173.6 2760.18   190.8 2759.83
   204.82753.806     208 2753.02   223.4  2753.8   233.8 2755.91   246.3 2755.34
   261.7 2757.92   277.1 2759.03   314.1 2757.83   332.7 2755.59     345 2758.12
   368.1 2760.56   375.3 2763.16   403.6 2779.31   419.8 2785.86   431.9 2794.81
   439.7 2798.99   464.2 2806.01   476.3  2807.9   484.4 2812.46   496.2 2816.58
#Mann= 3 ,-1,0
       0      .1       0   204.8    .045       0   223.4      .1       0
#XS Ineff= 2 , 0
                          280.05          2763.7
Permanent Ineff=
       F       F
Bank Sta=204.8,223.4
XS Rating Curve= 0 ,0
Exp/Cntr(USF)=0,0
Exp/Cntr=0.3,0.1

Type RM Length L Ch R = 1 ,8781    ,290,290.6,279.2
XS GIS Cut Line= 2
2231876.41552148624061.6182566682232288.16862923 623859.73930578
#Sta/Elev= 30
       0 2798.13    12.1 2793.96    21.1 2789.13    35.4 2786.76    57.6 2777.56
    93.3 2754.36   111.1 2746.29   124.5 2746.22   137.7 2744.05   160.1 2745.46
   164.6 2746.09   177.9 2752.09   186.8 2752.69   240.3 2747.88   245.3  2746.5
   254.2 2739.84   257.2 2739.32   280.4 2738.69  281.69 2739.31   293.8 2742.56
     311 2743.06   320.5 2740.86   333.8 2741.17   342.8 2747.62   360.6 2767.18
   382.6 2786.99   391.7 2792.83   409.6 2798.89   422.9 2800.25   458.6 2810.13
#Mann= 3 ,-1,0
       0      .1       0   257.2    .045       0  281.69      .1       0
Bank Sta=257.2,281.69
XS Rating Curve= 0 ,0
Exp/Cntr(USF)=0,0
Exp/Cntr=0.3,0.1

Type RM Length L Ch R = 1 ,8490    ,252.9,257.4,257.9
XS GIS Cut Line= 4
2232027.09084726624305.1643321682232117.43267719624264.364796074
2232200.48887566 624093.881020252232334.54449426624009.367695483
#Sta/Elev= 30
       0 2786.07      10 2784.13    19.4 2780.46    45.1 2773.25    55.2  2766.5
      67 2761.01    99.1    2738   105.4 2737.23   120.5 2740.05   130.5 2733.78
   154.4 2734.04   157.4 2733.22     165 2728.78   182.8 2726.48   191.7 2725.92
  202.73 2726.48   229.2 2732.73   262.9 2734.95   278.9 2737.29   288.8 2741.48
   297.9 2747.28   326.2  2769.5   329.7 2771.19   367.4 2777.08   387.7 2781.59
   397.2 2784.13   411.3 2789.96   422.5 2790.62     435 2796.17   447.2 2799.68
#Mann= 3 ,-1,0
       0      .1       0   182.8    .045       0  202.73      .1       0
Bank Sta=182.8,202.73
XS Rating Curve= 0 ,0
Exp/Cntr(USF)=0,0
Exp/Cntr=0.3,0.1

Type RM Length L Ch R = 1 ,8233    ,222.2,222.1,222
XS GIS Cut Line= 2
2232191.74611793624463.9910976792232458.40022883624188.594229041
#Sta/Elev= 30
       0 2780.29    17.9 2779.83    29.4 2776.03    40.9 2773.53      54 2768.98
    63.9 2764.21    98.4 2743.42   112.6 2732.51   121.4 2726.56   126.8 2724.42
   138.6 2723.97   150.1  2718.8   161.6 2718.17  170.09  2718.8   182.1 2722.95
   193.2 2724.26   204.4 2729.42   228.6 2731.25   239.9 2733.42   256.9 2740.81
   265.1 2745.55   271.2 2747.99   276.7 2751.51     305  2759.4   324.8 2767.73
   336.1 2769.55   344.6 2774.97   355.9 2780.49   365.8 2784.68   383.3 2790.56
#Mann= 3 ,-1,0
       0      .1       0   150.1    .045       0  170.09      .1       0
Bank Sta=150.1,170.09
XS Rating Curve= 0 ,0
Exp/Cntr(USF)=0,0
Exp/Cntr=0.3,0.1

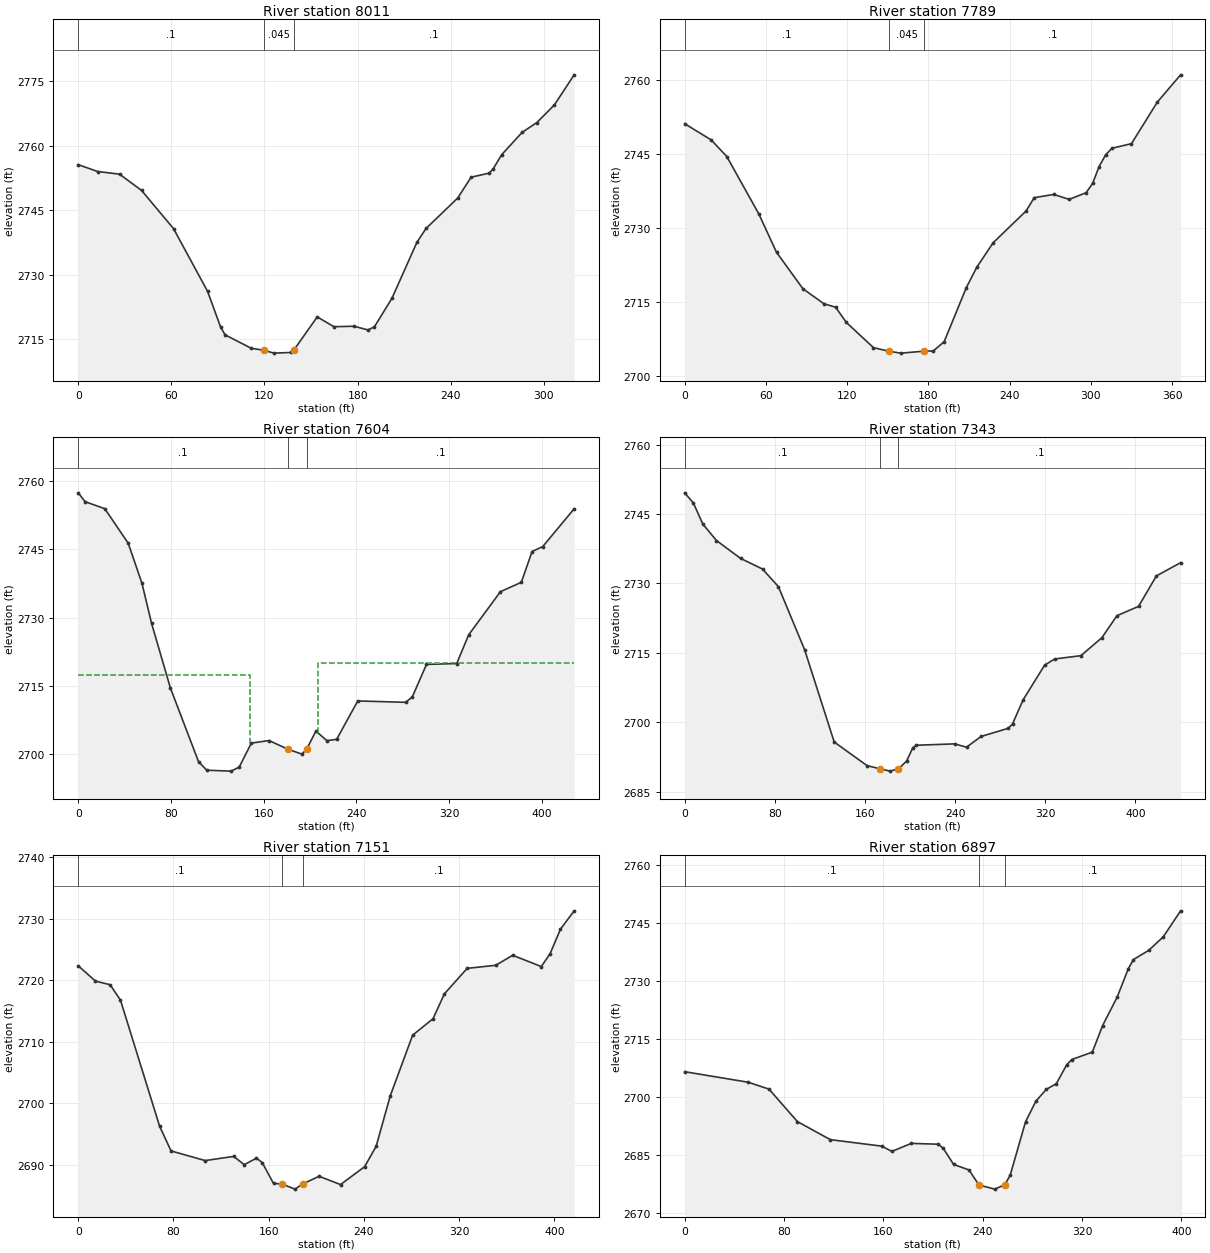
Type RM Length L Ch R = 1 ,8011    ,208.6,222.1,230.7
XS GIS Cut Line= 2
2232373.88690407624596.5895899862232593.91297372 624364.90651002
#Sta/Elev= 30
       0 2755.63    12.5 2754.03    26.6 2753.42    40.8 2749.64    61.4 2740.75
    83.3 2726.19    91.7  2717.9    94.6 2716.04   111.5 2712.92   119.5 2712.46
   126.1 2711.79     137 2711.94  138.982712.535     154 2720.22   164.7 2717.94
   177.6 2718.04   186.7 2717.19   190.8  2717.9   202.1 2724.53   218.2 2737.56
   224.1 2740.79   244.5 2747.87   253.1 2752.71   264.7 2753.65   267.2 2754.56
   272.8 2757.94     286 2763.14   295.5 2765.42   306.8 2769.54   319.5 2776.52
#Mann= 3 ,-1,0
       0      .1       0   119.5    .045       0  138.98      .1       0
Bank Sta=119.5,138.98
XS Rating Curve= 0 ,0
Exp/Cntr(USF)=0,0
Exp/Cntr=0.3,0.1

Type RM Length L Ch R = 1 ,7789    ,188.8,185,182.4
XS GIS Cut Line= 3
2232413.21276427624664.1556420572232656.55285455624684.555410104
2232758.55169479624617.527600806
#Sta/Elev= 30
       0 2751.09    19.6 2747.79    31.1 2744.43    54.7 2732.81    67.8 2725.01
    87.3 2717.61   102.9 2714.55   111.4 2713.87   119.4 2710.77   139.4 2705.66
  150.85 2704.93   159.5 2704.55   176.72704.939   183.6    2705   191.6 2706.87
     208 2717.86   215.7 2721.97   227.8 2726.95   252.1 2733.38   258.1 2736.08
   272.5 2736.74   283.9 2735.73   296.4 2737.09   301.2 2738.96     306  2742.4
   310.8 2744.75   315.5 2746.11   329.9 2747.04     349 2755.47   366.2    2761
#Mann= 3 ,-1,0
       0      .1       0  150.85    .045       0   176.7      .1       0
Bank Sta=150.85,176.7
XS Rating Curve= 0 ,0
Exp/Cntr(USF)=0,0
Exp/Cntr=0.3,0.1

Type RM Length L Ch R = 1 ,7604    ,263.1,260.9,256.9
BEGIN DESCRIPTION:
IFA needed to wet channel
END DESCRIPTION:
XS GIS Cut Line= 3
2232417.60069274624889.4719740922232622.55414431624857.176880314
 2232816.0068298624751.521607467
#Sta/Elev= 30
       0 2757.44       6 2755.49    22.9 2753.95    43.1 2746.37      55 2737.54
    63.3  2728.7    79.5 2714.52   103.8 2698.28   110.9 2696.39   131.9 2696.19
   138.9 2697.07   149.4 2702.36   164.6 2702.92   181.1    2701   192.9 2699.94
     197 2700.96   205.1 2705.01   214.6 2702.89     223  2703.2   241.2 2711.64
   282.6 2711.33   288.3 2712.55   300.5 2719.68   326.6 2719.87   336.9 2726.19
   364.3 2735.69   382.3 2737.74   391.6 2744.52   400.8 2745.61   427.9 2753.93
#Mann= 3 ,-1,0
       0      .1       0   181.1    .045       0     197      .1       0
#XS Ineff= 2 , 0
          148.38  2717.4  206.94         2719.97
Permanent Ineff=
       F       F
Bank Sta=181.1,197
XS Rating Curve= 0 ,0
Exp/Cntr(USF)=0,0
Exp/Cntr=0.3,0.1

Type RM Length L Ch R = 1 ,7343    ,192,192.3,191.1
XS GIS Cut Line= 3
2232484.62850204 625132.812064372232564.77044794625115.326548901
2232872.22409493624931.728636476
#Sta/Elev= 30
       0  2749.6     7.7 2747.41    16.1 2742.85    28.2 2739.29    49.7 2735.41
    69.1 2733.12    83.2 2729.31   106.5 2715.64   132.7 2695.73   161.9 2690.62
   173.6 2689.93   182.3 2689.44   189.7 2689.94   196.9  2691.6   202.5 2694.52
   205.7 2695.04   239.7 2695.33   250.1 2694.61     263 2696.93   287.3 2698.71
     291 2699.67   300.3 2704.84   319.4 2712.35   328.3 2713.68   351.6  2714.4
   370.2 2718.27   383.6 2723.04   402.8 2725.06   418.6 2731.64   440.1  2734.5
#Mann= 3 ,-1,0
       0      .1       0   173.6    .045       0   189.7      .1       0
Bank Sta=173.6,189.7
XS Rating Curve= 0 ,0
Exp/Cntr(USF)=0,0
Exp/Cntr=0.3,0.1

Type RM Length L Ch R = 1 ,7151    ,249.6,253.8,256.6
XS GIS Cut Line= 2
2232590.99872114 625325.152734532232939.25190423625096.383907143
#Sta/Elev= 30
       0 2722.36    14.5 2719.87    26.8 2719.28    35.5 2716.78    68.4 2696.28
      78 2692.27   106.7  2690.7   130.6 2691.38   139.5 2690.04   149.8 2691.09
   154.6 2690.38   164.1 2686.98   171.2  2686.9   182.1 2686.06   188.6 2686.89
   202.4 2688.15   220.4  2686.8   240.6  2689.7   250.3    2693   262.2 2701.23
     281 2711.08   298.1 2713.75   307.7  2717.8   326.8 2721.94   350.8 2722.44
   365.1 2724.07   389.1 2722.23   396.5 2724.33   405.2 2728.31   416.7 2731.29
#Mann= 3 ,-1,0
       0      .1       0   171.2    .045       0   188.6      .1       0
Bank Sta=171.2,188.6
XS Rating Curve= 0 ,0
Exp/Cntr(USF)=0,0
Exp/Cntr=0.3,0.1

Type RM Length L Ch R = 1 ,6897    ,339.9,343.7,351.8
XS GIS Cut Line= 2
2232666.76928817625438.8085850792233052.90775478625336.809744842
#Sta/Elev= 30
       0 2706.55    51.1 2703.83    67.9 2702.04    90.8 2693.63   117.3 2688.96
   158.7 2687.28   166.9 2685.92   182.5 2687.99   204.2 2687.78   208.3 2686.69
   216.6 2682.54     229 2681.11     2372677.212   249.7 2676.15   257.8 2677.28
   262.1 2679.71   274.5 2693.57   282.8 2698.89   291.1 2701.95   299.3 2703.45
   307.6 2708.32   311.7  2709.7   328.3 2711.62   336.6 2718.51   348.3 2725.85
   357.3 2733.23   361.4 2735.58   373.8 2737.99   385.4 2741.46   399.4  2748.2
#Mann= 3 ,-1,0
       0      .1       0     237    .045       0   257.8      .1       0
Bank Sta=237,257.8
XS Rating Curve= 0 ,0
Exp/Cntr(USF)=0,0
Exp/Cntr=0.3,0.1