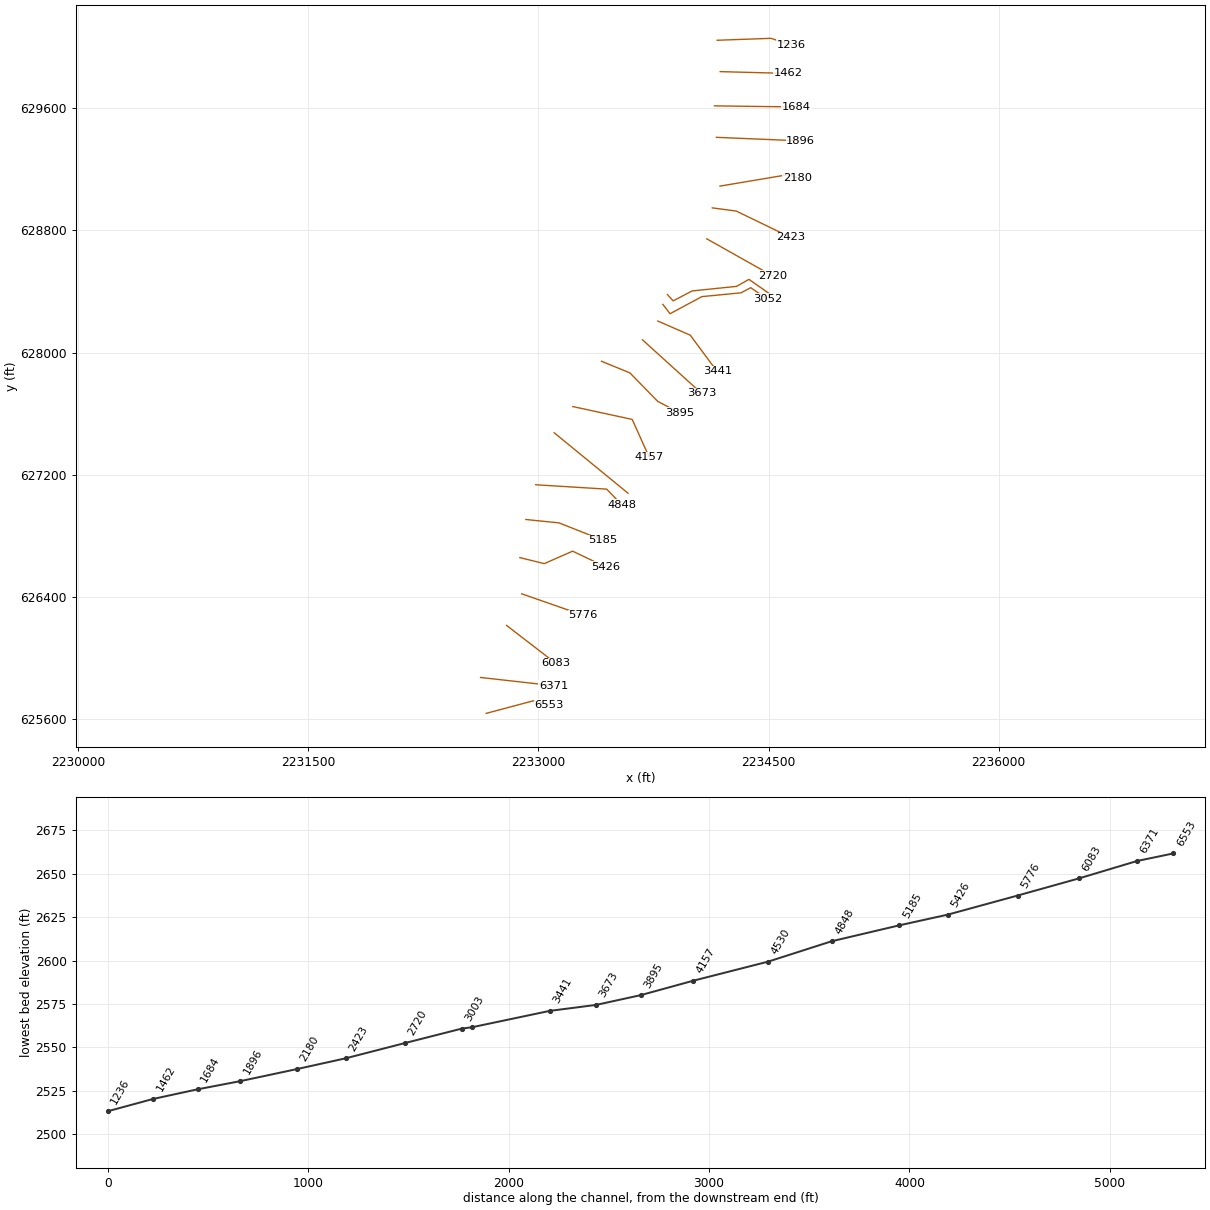
HEC-RAS study ROCKYRN.prj: ROCKYRN

--- ROCKYRN.g01 (geometry) --- (continued)

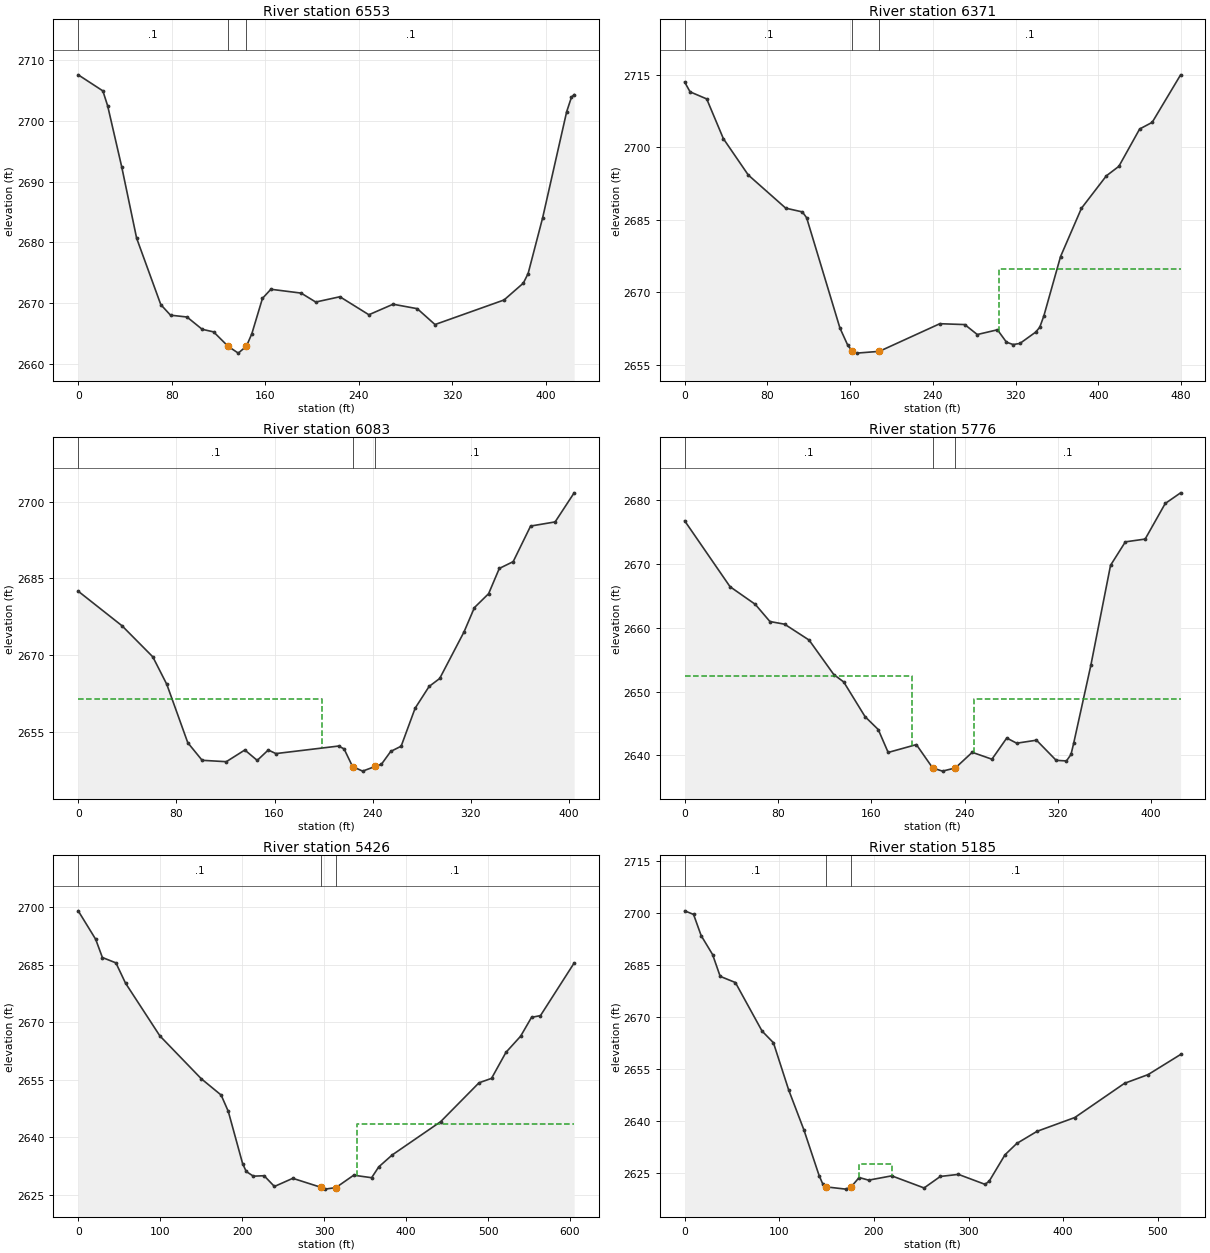
Type RM Length L Ch R = 1 ,6553    ,186,181.7,179.7
XS GIS Cut Line= 3
2232659.83297166625639.5587323822232967.74944062625722.006311503
2233070.38826361 625696.76725667
#Sta/Elev= 30
       0 2707.55    21.1 2704.91    25.2 2702.45    37.2 2692.45      50 2680.69
    70.7 2669.76      79 2668.03    93.1 2667.73   106.1 2665.71   115.9 2665.28
   128.3 2662.91     137 2661.79  143.992662.932   148.6 2664.97   157.7 2670.79
   164.9 2672.29   190.8 2671.66   203.3 2670.19     224 2671.06   248.8  2668.1
   269.5 2669.83   290.2  2669.1   305.4 2666.49   364.5 2670.53     381  2673.3
   385.1 2674.88   397.5 2684.02   418.1 2701.49   422.2 2703.87   424.5  2704.3
#Mann= 3 ,-1,0
       0      .1       0   128.3    .045       0  143.99      .1       0
Bank Sta=128.3,143.99
XS Rating Curve= 0 ,0
Exp/Cntr(USF)=0,0
Exp/Cntr=0.3,0.1

Type RM Length L Ch R = 1 ,6371    ,296,288.1,281.2
XS GIS Cut Line= 2
 2232623.0554995625874.4893455162233099.53579603 625820.57567282
#Sta/Elev= 30
       0 2713.52     5.2  2711.5    21.3 2710.03    37.4 2701.81    61.5 2694.28
    97.7 2687.42   113.8 2686.64   117.9 2685.44   150.1 2662.61   157.7 2659.03
   162.1 2657.81   166.2 2657.41  188.182657.777   246.7  2663.5   270.8 2663.32
   282.9 2661.26   302.4 2662.24   311.1 2659.68   317.5 2659.19   324.1 2659.41
   339.3 2661.75   343.3 2662.76   347.3 2665.14   363.4 2677.39   383.6 2687.39
   407.7 2694.11   419.8 2696.08   439.9 2703.81     452 2705.18   479.5 2715.02
#Mann= 3 ,-1,0
       0      .1       0   162.1    .045       0  188.18      .1       0
#XS Ineff= 2 , 0
                          303.97         2674.74
Permanent Ineff=
       F       F
Bank Sta=162.1,188.18
XS Rating Curve= 0 ,0
Exp/Cntr(USF)=0,0
Exp/Cntr=0.3,0.1

Type RM Length L Ch R = 1 ,6083    ,303.1,306.9,309.2
XS GIS Cut Line= 2
2232792.75866045626215.009182571  2233112.453355625967.666445209
#Sta/Elev= 30
       0 2682.52    35.7 2675.78    60.8 2669.72    72.2 2664.36    89.3 2652.98
     101 2649.55   120.7 2649.28   135.8 2651.56   145.9 2649.53   154.9 2651.56
   161.1 2650.86   212.2 2652.33   216.7 2651.77  223.592648.333   231.8 2647.44
     242 2648.35   247.1 2648.77   254.7 2651.28   263.2  2652.3   274.6 2659.71
     286 2663.95   294.6  2665.5   314.5 2674.61   322.9 2679.32   334.5 2682.04
   343.2 2686.96   354.5 2688.28   368.7 2695.22   388.7 2696.03   404.2  2701.7
#Mann= 3 ,-1,0
       0      .1       0  223.59    .045       0     242      .1       0
#XS Ineff= 2 , 0
          198.88 2661.44
Permanent Ineff=
       F       F
Bank Sta=223.59,242
XS Rating Curve= 0 ,0
Exp/Cntr(USF)=0,0
Exp/Cntr=0.3,0.1

Type RM Length L Ch R = 1 ,5776    ,342,350,355.4
XS GIS Cut Line= 2
 2232891.4600268626421.6050892082233292.86568457626281.078439728
#Sta/Elev= 30
       0 2676.78    38.9 2666.45    60.5 2663.69    73.1 2660.99    85.7 2660.57
   106.7 2658.08   127.9 2652.67   136.4 2651.51   154.7 2646.07     166 2644.05
   174.5 2640.46   198.7 2641.69   212.7 2638.02   221.1 2637.53  232.14 2638.03
   246.6 2640.48   263.5  2639.4   276.2 2642.72   284.7 2641.91   301.7 2642.38
   318.6 2639.22   327.4 2639.13   331.3 2640.14   333.6 2641.91   348.3 2654.11
   365.2  2669.8   377.9 2673.48   394.9 2673.92   412.1  2679.5   425.3 2681.17
#Mann= 3 ,-1,0
       0      .1       0   212.7    .045       0  232.14      .1       0
#XS Ineff= 2 , 0
          195.31 2652.45   248.4         2648.88
Permanent Ineff=
       F       F
Bank Sta=212.7,232.14
XS Rating Curve= 0 ,0
Exp/Cntr(USF)=0,0
Exp/Cntr=0.3,0.1

Type RM Length L Ch R = 1 ,5426    ,249.5,241.4,235.6
XS GIS Cut Line= 4
2232879.50972638626658.4232890452233038.33649189 626619.08087924
 2233223.3915306626700.6799514292233439.04622139626597.223984904
#Sta/Elev= 30
       0 2699.09    21.3 2691.67    29.5 2686.91      46 2685.51    57.7 2680.23
    99.6 2666.47   150.2 2655.27   174.4 2651.02   183.1 2646.77   200.6 2633.13
     205 2631.08   213.7 2629.86   226.8 2629.98   239.4 2627.17   261.8  2629.3
   296.8 2626.91   301.2 2626.48  314.462626.884   336.1 2630.11     358 2629.46
   366.7 2632.29   383.2 2635.41   442.2 2644.08     489 2654.22   504.3 2655.38
   521.9 2662.17   539.8 2666.38   553.1  2671.3     564 2671.75   605.1 2685.48
#Mann= 3 ,-1,0
       0      .1       0   296.8    .045       0  314.46      .1       0
#XS Ineff= 2 , 0
                          339.64         2643.45
Permanent Ineff=
       F       F
Bank Sta=296.8,314.46
XS Rating Curve= 0 ,0
Exp/Cntr(USF)=0,0
Exp/Cntr=0.3,0.1

Type RM Length L Ch R = 1 ,5185    ,344.3,337.4,334.7
XS GIS Cut Line= 3
2232918.85213618626907.7242812592233135.37606169626885.362243345
2233420.10357963626772.079139594
#Sta/Elev= 30
       0 2700.58     9.4 2699.54    17.4 2693.44    29.5 2687.97    37.5 2681.69
    53.6  2679.9    81.8  2665.9    93.8 2662.54   109.9 2648.93     126 2637.41
   142.1 2624.22   146.1 2621.71  149.37 2620.98   170.2 2620.33  176.03 2621.02
  184.39 2623.68   194.4 2622.92   218.8 2624.16     253 2620.67   270.2 2623.99
   289.3 2624.58   317.5  2621.7   321.9 2622.66   338.5 2630.23   350.9 2633.49
   372.4    2637   412.3 2640.98   464.8 2650.84   489.7 2653.35   524.1 2659.16
#Mann= 3 ,-1,0
       0      .1       0  149.37    .045       0  176.03      .1       0
#XS Ineff= 1 ,-1
  184.61  219.332627.534
Permanent Ineff=
       F
Bank Sta=149.37,176.03
XS Rating Curve= 0 ,0
Exp/Cntr(USF)=0,0
Exp/Cntr=0.3,0.1

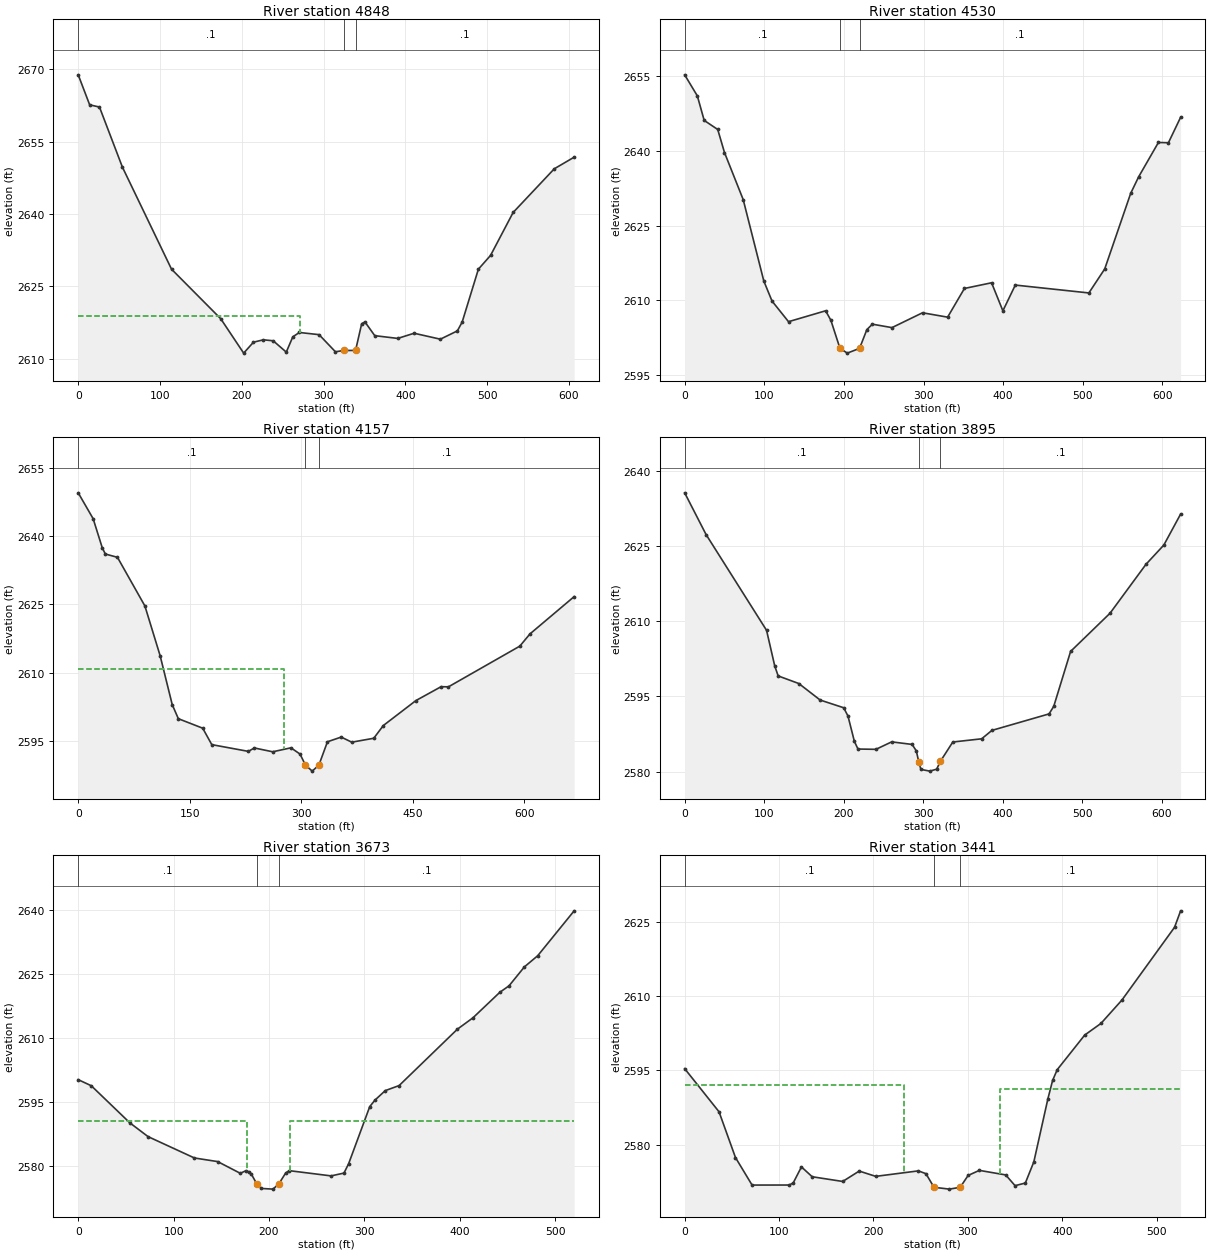
Type RM Length L Ch R = 1 ,4848    ,328.2,317.5,309
XS GIS Cut Line= 3
2232982.24319889627134.9475312832233444.95920416627106.343269139
2233544.23281983627003.704446152
#Sta/Elev= 30
       0 2668.84      14 2662.62      26 2662.16      54 2649.72   114.1 2628.55
   174.3 2618.27   202.3 2611.15   214.3 2613.42   226.4 2613.91   238.4 2613.71
   254.4 2611.36   262.4 2614.53   270.4 2615.43   294.5 2614.98   314.5 2611.43
   324.8  2611.7  339.112611.707   346.6 2617.24   350.6 2617.62   362.6 2614.77
   390.7  2614.2   410.7 2615.27   442.8 2614.04   463.6 2615.76   469.5  2617.6
   489.3 2628.55   504.2 2631.41   531.8 2640.31   582.1 2649.36   606.4 2651.77
#Mann= 3 ,-1,0
       0      .1       0   324.8    .045       0  339.11      .1       0
#XS Ineff= 2 , 0
          270.63 2618.77
Permanent Ineff=
       F       F
Bank Sta=324.8,339.11
XS Rating Curve= 0 ,0
Exp/Cntr(USF)=0,0
Exp/Cntr=0.3,0.1

Type RM Length L Ch R = 1 ,4530    ,370.7,373.5,377.7
XS GIS Cut Line= 2
2233103.39066209627474.8334696992233584.61530757627079.421610651
#Sta/Elev= 30
       0 2655.25    15.9 2651.02    24.5  2646.1    41.5 2644.28      50 2639.65
    73.5  2630.2    99.4 2613.85   109.7 2609.84   130.4  2605.7     177 2607.89
   183.6 2605.98     195 2600.35   204.2 2599.39   219.62600.344   228.8 2604.11
   235.7  2605.2   260.3 2604.51   298.7 2607.49   330.2 2606.61   351.3 2612.37
   385.4 2613.51   399.6 2607.88   415.2 2613.05   507.6 2611.47   527.5 2616.29
   560.1 2631.46   570.1 2634.78   594.9 2641.67   607.5 2641.62   622.8 2646.73
#Mann= 3 ,-1,0
       0      .1       0     195    .045       0   219.6      .1       0
Bank Sta=195,219.6
XS Rating Curve= 0 ,0
Exp/Cntr(USF)=0,0
Exp/Cntr=0.3,0.1

Type RM Length L Ch R = 1 ,4157    ,266.8,261.4,254.4
XS GIS Cut Line= 3
2233224.53812528627646.4590425622233611.53696605627562.328859786
2233722.58880732627314.986122424
#Sta/Elev= 30
       0 2649.53    20.1 2643.84    32.4 2637.43    36.5 2636.09    52.8 2635.36
    89.7 2624.68   110.2 2613.75   126.5 2602.99   134.7 2599.91   167.5 2597.82
   179.7 2594.21   228.9 2592.73     237 2593.48   261.6 2592.64   286.2 2593.51
   298.4 2592.14  305.722589.717   314.8 2588.39   323.82589.719   335.3 2594.84
   353.8 2595.87     368 2594.75   397.6 2595.61   410.5 2598.41   454.3 2603.89
   488.2 2606.94   498.1 2606.91   594.1 2615.85   607.8 2618.54   667.2 2626.73
#Mann= 3 ,-1,0
       0      .1       0  305.72    .045       0   323.8      .1       0
#XS Ineff= 2 , 0
          277.47 2610.78
Permanent Ineff=
       F       F
Bank Sta=305.72,323.8
XS Rating Curve= 0 ,0
Exp/Cntr(USF)=0,0
Exp/Cntr=0.3,0.1

Type RM Length L Ch R = 1 ,3895    ,221.9,222.6,223.4
XS GIS Cut Line= 4
2233411.30713105627942.5972859342233596.39353315627866.880121436
2233778.11472795627680.1111156732233922.81864233627604.393951174
#Sta/Elev= 30
       0 2635.64    26.9 2627.32     103  2608.2   113.3 2601.09   117.6  2599.1
   143.6 2597.58   170.4 2594.29     200 2592.75   205.4 2591.11   213.5 2586.03
     218 2584.51   240.6 2584.45   260.4 2585.94   286.1 2585.43   291.4 2584.14
   294.4 2582.01   297.2 2580.44   308.4  2580.1     317 2580.49  321.592582.033
   337.3 2585.91   373.6 2586.55   386.5 2588.23   458.4 2591.52   464.3 2593.03
   485.5 2603.99   535.1 2611.61   580.3 2621.37   602.8 2625.22   623.9  2631.4
#Mann= 3 ,-1,0
       0      .1       0   294.4    .045       0  321.59      .1       0
Bank Sta=294.4,321.59
XS Rating Curve= 0 ,0
Exp/Cntr(USF)=0,0
Exp/Cntr=0.3,0.1

Type RM Length L Ch R = 1 ,3673    ,233,231.9,228.9
XS GIS Cut Line= 2
 2233678.0149328628083.4927997742234062.69627312627733.782490393
#Sta/Elev= 30
       0 2600.19    13.7 2598.76    54.1 2590.05    73.2 2586.81   121.8 2581.79
   146.2 2580.94   169.9 2578.19   175.9 2578.81   178.7 2578.55   181.6 2577.96
   187.2 2575.69   192.1 2574.63   204.2 2574.47  210.332575.712   217.5 2578.26
   221.2 2578.81   265.1 2577.58   278.6 2578.24   283.5 2580.45   305.6 2593.85
   311.1 2595.39   321.9 2597.62   336.4  2598.8   397.5 2612.05   413.8 2614.72
   442.1 2620.74   451.6 2622.23   467.8  2626.7   481.7 2629.31   519.9 2639.86
#Mann= 3 ,-1,0
       0      .1       0   187.2    .045       0  210.33      .1       0
#XS Ineff= 2 , 0
          176.75 2590.52  221.81         2590.52
Permanent Ineff=
       F       F
Bank Sta=187.2,210.33
XS Rating Curve= 0 ,0
Exp/Cntr(USF)=0,0
Exp/Cntr=0.3,0.1

Type RM Length L Ch R = 1 ,3441    ,371.2,388.4,395.1
BEGIN DESCRIPTION:
Structure XS 4
END DESCRIPTION:
XS GIS Cut Line= 3
2233778.88552015628205.8801881852233990.16606353628113.146194033
2234165.11782569627876.053095581
#Sta/Elev= 30
       0 2595.37    36.4 2586.65    53.8 2577.41    71.4 2571.84   110.8 2571.85
     115 2572.28   123.7 2575.51   135.1 2573.52   167.4 2572.57   184.9 2574.67
   202.4  2573.6   247.6 2574.71   255.6 2574.14  264.122571.395   280.4 2571.02
  291.86 2571.39   300.3 2573.79   312.2 2574.81   340.1 2573.89     350 2571.72
   360.9 2572.25   369.9 2576.53   384.8 2589.28   389.8    2593   394.7 2595.17
   423.8 2602.16     441 2604.51   463.2 2609.23     519 2623.95   525.4 2627.27
#Mann= 3 ,-1,0
       0      .1       0  264.12    .045       0  291.86      .1       0
#XS Ineff= 2 , 0
           232.2 2592.03  334.44         2591.31
Permanent Ineff=
       F       F
Bank Sta=264.12,291.86
XS Rating Curve= 0 ,0
Exp/Cntr(USF)=0,0
Exp/Cntr=0.3,0.1

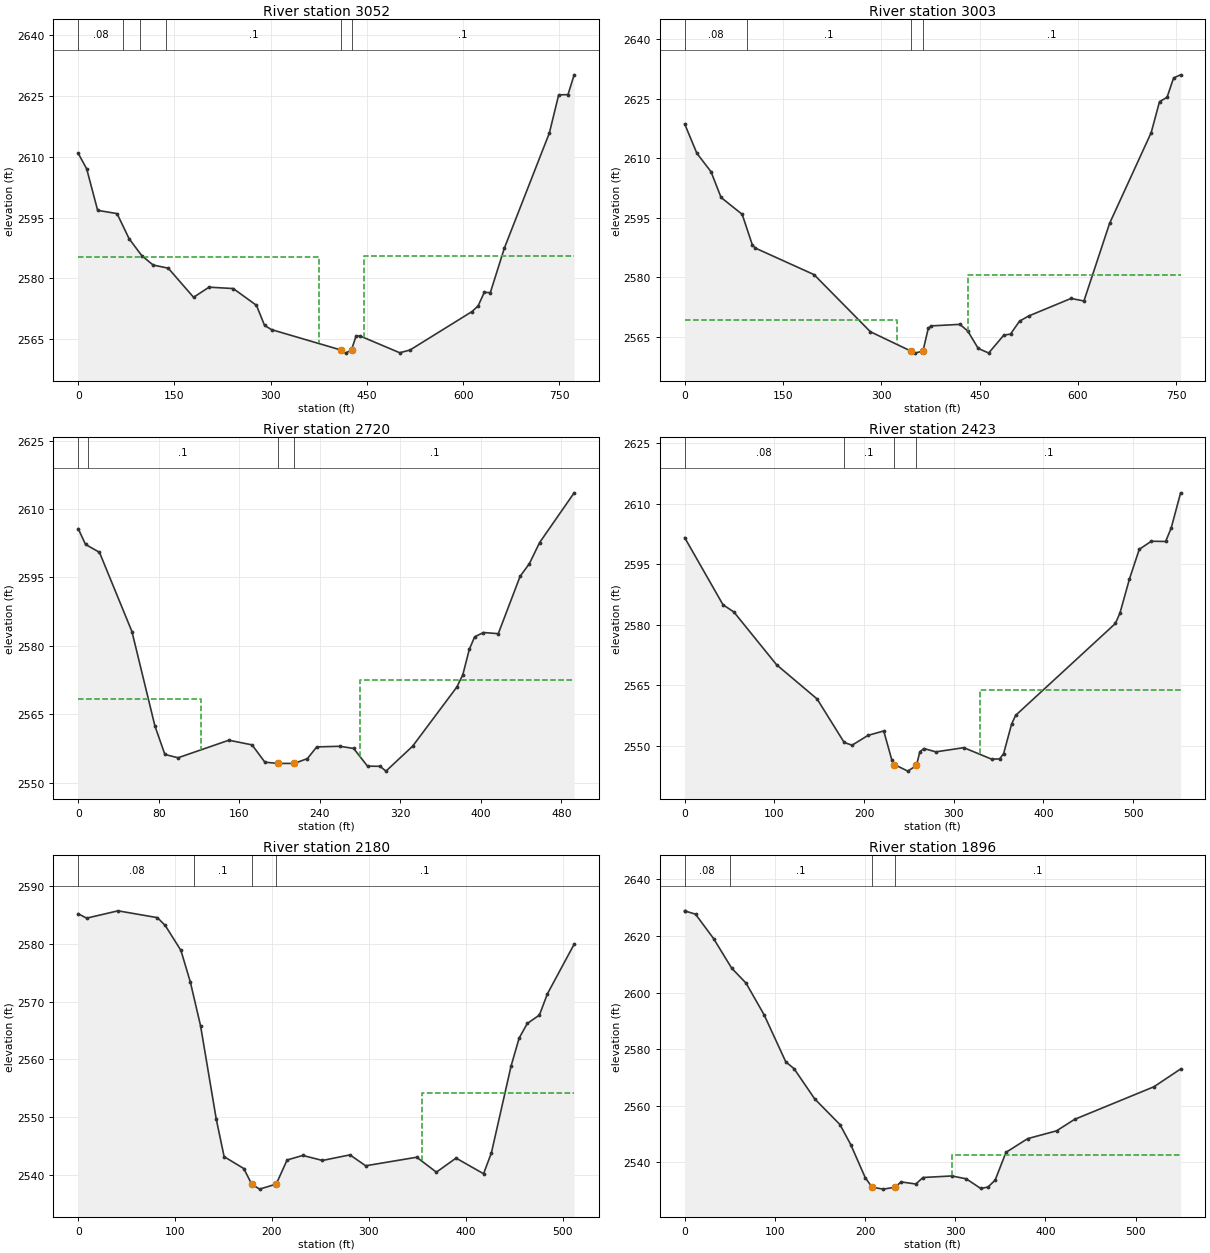
Type RM Length L Ch R = 1 ,3052    ,49,49,49.1
BEGIN DESCRIPTION:
Structure XS 3
END DESCRIPTION:
XS GIS Cut Line= 6
2233811.39021913628314.8665318282233858.23522649628253.681216098
2234065.69168763628365.5356214162234320.94917669628390.392155931
2234384.04653354628423.8528754712234492.07685662628350.239292484
#Sta/Elev= 30
       0 2610.89    13.2 2607.05    30.3 2596.81    60.5 2596.01    79.3 2589.82
    99.1 2585.62   116.8 2583.31   140.3 2582.54   179.8 2575.35   203.9 2577.85
   241.6 2577.51   277.8 2573.37   290.4 2568.41   301.3 2567.37     409 2562.36
   416.9 2561.57  425.922562.398   432.9 2565.73   438.7 2565.84   501.1 2561.66
   517.1 2562.34   613.7 2571.83   623.2 2573.21   632.8 2576.56   642.3 2576.52
   664.3 2587.56   734.3 2615.92   748.8 2625.32   763.3 2625.37   772.9 2630.26
#Mann= 6 ,-1,0
       0     .08       0      70      .1       0   97.06     .08       0
  137.06      .1       0     409    .045       0  425.92      .1       0
#XS Ineff= 2 , 0
          374.87 2585.24  445.92         2585.52
Permanent Ineff=
       F       F
Bank Sta=409,425.92
XS Rating Curve= 0 ,0
Exp/Cntr(USF)=0,0
Exp/Cntr=0.3,0.1

Type RM Length L Ch R = 1 ,3003    ,288.9,283.7,277.7
BEGIN DESCRIPTION:
Structure XS 2
END DESCRIPTION:
XS GIS Cut Line= 6
2233841.02685644628378.9199092322233878.31165821628337.811025226
2234002.59433079628402.8204231892234291.31253938628432.457060495
2234372.57428684628478.3460472922234516.93339114628377.007868115
#Sta/Elev= 30
       0 2618.59    18.6  2611.2    40.2 2606.55    55.5 2600.07    87.7 2595.82
   103.1 2588.17   107.7 2587.32   197.4 2580.62   283.3 2566.23  344.842561.377
   351.1 2560.84   363.6 2561.38   371.6 2567.09   375.6  2567.7   419.8 2568.09
   431.8 2566.43   447.8 2562.03   463.8 2560.87   486.9 2565.38   497.1 2565.64
   510.9 2568.91   524.7 2570.19   589.4 2574.62   609.1 2573.98   648.2 2593.52
   711.7 2616.41   724.4 2624.21   735.9  2625.3   745.9 2630.19   756.6 2630.97
#Mann= 4 ,-1,0
       0     .08       0    95.5      .1       0  344.84    .045       0
   363.6      .1       0
#XS Ineff= 2 , 0
          323.95 2569.09  432.64         2580.41
Permanent Ineff=
       F       F
Bank Sta=344.84,363.6
XS Rating Curve= 0 ,0
Exp/Cntr(USF)=0,0
Exp/Cntr=0.3,0.1

Type RM Length L Ch R = 1 ,2720    ,294.9,296.6,292.6
BEGIN DESCRIPTION:
Structure XS 1
END DESCRIPTION:
XS GIS Cut Line= 2
 2234097.8094225628743.5166259642234526.87335466628501.221699568
#Sta/Elev= 30
       0 2605.68     7.3 2602.22    21.1  2600.5    53.4 2583.11    76.2 2562.43
    86.1 2556.17    99.2 2555.44   149.7 2559.29   172.7 2558.27   185.5 2554.47
  198.63  2554.2   214.8  2554.2   227.8 2555.27     237 2557.82     260 2557.96
   273.7 2557.48   287.5  2553.6     300 2553.57   305.8 2552.51   332.3 2557.98
   376.3 2570.97   382.2 2573.68   388.6 2579.19   393.9 2581.96   402.7 2582.91
   417.4 2582.65   439.1 2595.23   448.3 2598.01   458.5 2602.64   492.8 2613.54
#Mann= 4 ,-1,0
       0     .08       0      10      .1       0  198.63    .045       0
   214.8      .1       0
#XS Ineff= 2 , 0
          122.38 2568.34  280.14         2572.57
Permanent Ineff=
       F       F
Bank Sta=198.63,214.8
XS Rating Curve= 0 ,0
Exp/Cntr(USF)=0,0
Exp/Cntr=0.3,0.1

Type RM Length L Ch R = 1 ,2423    ,236.9,243,251.9
XS GIS Cut Line= 3
2234133.86994043628945.9543251462234289.62623923 628925.23782076
2234645.63028209628752.267182138
#Sta/Elev= 30
       0 2601.62    42.7 2584.97    54.8 2583.18   102.5 2570.07   147.6  2561.6
   177.8 2550.81   186.6 2550.12   204.4 2552.56   221.9 2553.65   231.1 2546.34
   233.9 2545.32   248.8 2543.69  258.35  2545.1   262.2  2548.5   266.7  2549.3
     280 2548.47   311.2 2549.51   342.3 2546.65   351.2 2546.73   355.6 2548.06
   364.5 2555.39     369 2557.53   480.2 2580.32   485.3 2582.93   495.9 2591.39
   506.8 2598.71   520.2 2600.72   536.2 2600.66   542.4 2604.01   552.9 2612.73
#Mann= 4 ,-1,0
       0     .08       0  177.13      .1       0   233.9    .045       0
  258.35      .1       0
#XS Ineff= 2 , 0
                          329.24         2563.72
Permanent Ineff=
       F       F
Bank Sta=233.9,258.35
XS Rating Curve= 0 ,0
Exp/Cntr(USF)=0,0
Exp/Cntr=0.3,0.1

Type RM Length L Ch R = 1 ,2180    ,285.2,283.7,279.8
XS GIS Cut Line= 3
2234183.62220893629088.4503753462234622.78176302629162.484936189
2234686.72070193629143.976295978
#Sta/Elev= 30
       0 2585.23     8.7 2584.47    41.1 2585.74    81.7 2584.56    89.8 2583.21
     106 2578.88   115.7 2573.42   126.3  2565.8   142.5 2549.61   150.6 2543.12
   170.9 2541.06     179 2538.37   187.2 2537.49  204.382538.363   215.6 2542.54
   231.8 2543.33   252.1 2542.46   280.5 2543.43   296.7 2541.54   349.4 2543.02
   369.7 2540.43     390 2542.87   418.4 2540.16   426.5 2543.79   446.8 2558.84
   455.1 2563.67   463.5 2566.21     476 2567.66   484.3 2571.35   511.9 2579.96
#Mann= 4 ,-1,0
       0     .08       0     120      .1       0     179    .045       0
  204.38      .1       0
#XS Ineff= 2 , 0
                           354.8         2554.21
Permanent Ineff=
       F       F
Bank Sta=179,204.38
XS Rating Curve= 0 ,0
Exp/Cntr(USF)=0,0
Exp/Cntr=0.3,0.1

Type RM Length L Ch R = 1 ,1896    ,211.7,211.9,212.4
XS GIS Cut Line= 2
2234160.15000651629407.4884339742234709.67493349629384.385319451
#Sta/Elev= 30
       0 2628.92       0 2628.91      12 2627.74    32.1 2619.09    52.1 2608.66
    68.1 2603.34    88.1 2592.15   112.1 2575.53   121.3 2573.11   144.2 2562.42
   172.2 2553.35   184.2 2546.23   200.2  2534.6  207.78 2531.19   220.2 2530.51
   232.8 2531.15   240.2 2533.06   256.3 2532.32   264.3 2534.62   296.3 2535.17
   312.3 2534.15   328.3 2530.75   336.3 2531.23   344.3 2533.68   356.3  2543.5
   380.4 2548.37   412.4 2551.12   432.4 2555.18   520.5 2566.72     550    2573
#Mann= 4 ,-1,0
       0     .08       0      50      .1       0  207.78    .045       0
   232.8      .1       0
#XS Ineff= 2 , 0
                          296.65         2542.72
Permanent Ineff=
       F       F
Bank Sta=207.78,232.8
XS Rating Curve= 0 ,0
Exp/Cntr(USF)=0,0
Exp/Cntr=0.3,0.1

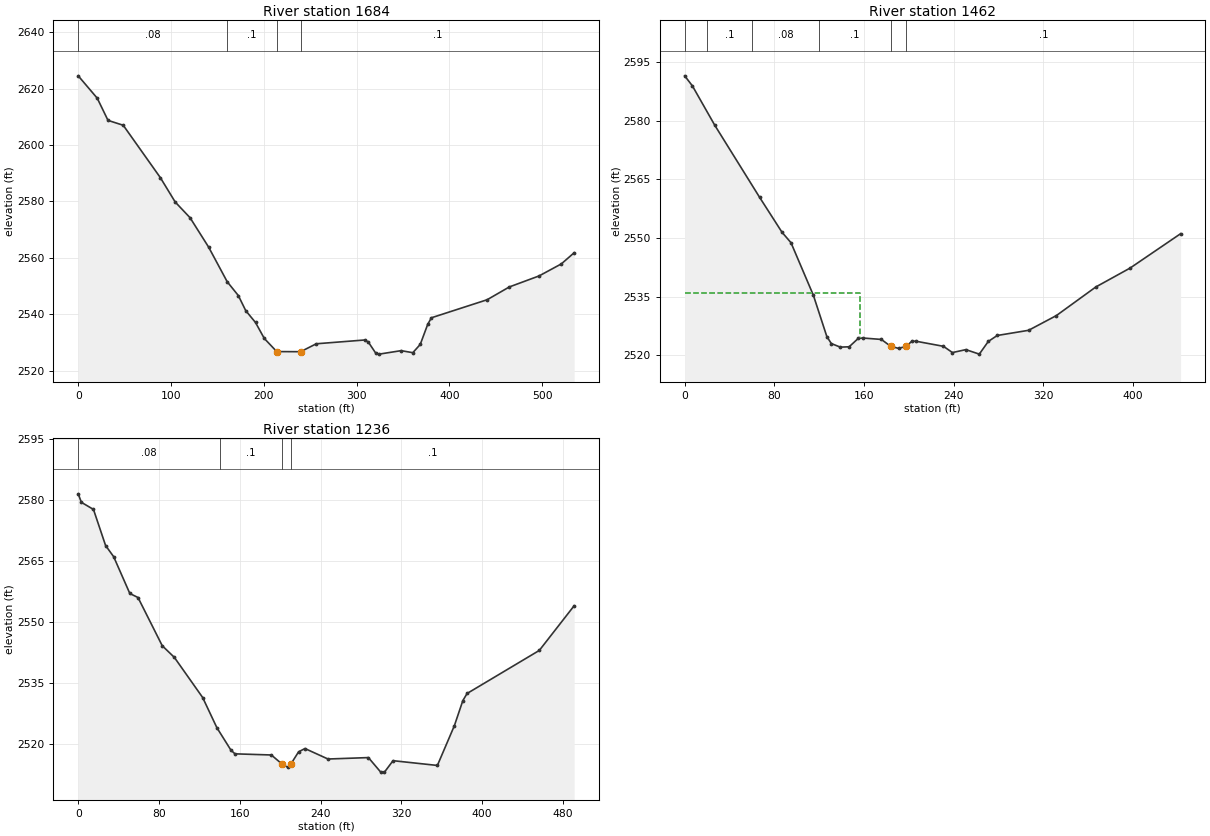
Type RM Length L Ch R = 1 ,1684    ,222.2,222.1,222
XS GIS Cut Line= 2
2234147.70481667629613.2733478612234681.98445601629606.077662483
#Sta/Elev= 30
       0 2624.52    20.5 2616.59    32.1 2608.72    48.5 2606.99    88.5 2588.41
   104.5 2579.77   120.5  2574.2   140.5 2563.78   160.5 2551.51   172.5  2546.6
   180.5 2541.24     191 2537.05   200.5 2531.38  213.872526.731   239.6 2526.69
   256.5  2529.5   308.5 2530.84   312.5 2530.13   320.5  2526.2   324.2 2525.83
   347.9 2527.06   360.5 2526.34   368.5 2529.28   376.5 2536.36   380.5 2538.72
   440.5 2545.11   464.5 2549.66   496.5 2553.56   520.5 2557.83   534.3 2561.78
#Mann= 4 ,-1,0
       0     .08       0     160      .1       0  213.87    .045       0
   239.6      .1       0
Bank Sta=213.87,239.6
XS Rating Curve= 0 ,0
Exp/Cntr(USF)=0,0
Exp/Cntr=0.3,0.1

Type RM Length L Ch R = 1 ,1462    ,225.4,226.2,226.5
XS GIS Cut Line= 2
2234185.30481259629837.2090020542234627.82957399629825.430776465
#Sta/Elev= 30
       0 2591.51     6.9 2588.93    26.9 2578.84    66.9  2560.4    86.9 2551.46
    94.9 2548.79   114.9 2535.32   126.9 2524.77   130.9 2522.98   138.9 2522.06
   146.8 2522.15   154.9 2524.28   158.9  2524.4   175.6 2524.03   183.8 2522.29
   190.9 2521.74  197.762522.266   202.9  2523.6   206.9 2523.55     231 2522.27
     239 2520.67     251 2521.42     263 2520.27     271 2523.51     279 2525.04
     307 2526.37   331.8 2530.14     367 2537.46   397.6  2542.3   442.7  2551.1
#Mann= 6 ,-1,0
       0     .08       0      20      .1       0      60     .08       0
     120      .1       0   183.8    .045       0  197.76      .1       0
#XS Ineff= 2 , 0
          156.68    2536
Permanent Ineff=
       F       F
Bank Sta=183.8,197.76
XS Rating Curve= 0 ,0
Exp/Cntr(USF)=0,0
Exp/Cntr=0.3,0.1

Type RM Length L Ch R = 1 ,1236    ,278.2,279.2,279.8
XS GIS Cut Line= 3
2234165.05828566630042.3853140442234515.84794785630054.977763456
2234648.96812734630011.803651187
#Sta/Elev= 30
       0 2581.52     3.1 2579.44    15.1 2577.69    27.1 2568.83    35.1 2566.08
    51.1 2557.05    59.2 2556.06    83.2 2544.22    95.2 2541.36   123.2 2531.51
   137.3 2524.09   151.2 2518.59   155.2 2517.68   191.2  2517.4  201.862515.158
   207.3 2514.41   210.5 2515.16   218.2 2518.18   224.5 2518.98   247.3 2516.41
   287.3 2516.76   299.3 2513.25   303.2 2513.19   311.7    2516   355.6 2514.83
   372.4 2524.58   380.8 2530.75     385  2532.5   456.5 2543.07     491 2554.04
#Mann= 4 ,-1,0
       0     .08       0     140      .1       0  201.86    .045       0
   210.5      .1       0
Bank Sta=201.86,210.5
XS Rating Curve= 0 ,0
Exp/Cntr(USF)=0,0
Exp/Cntr=0.3,0.1