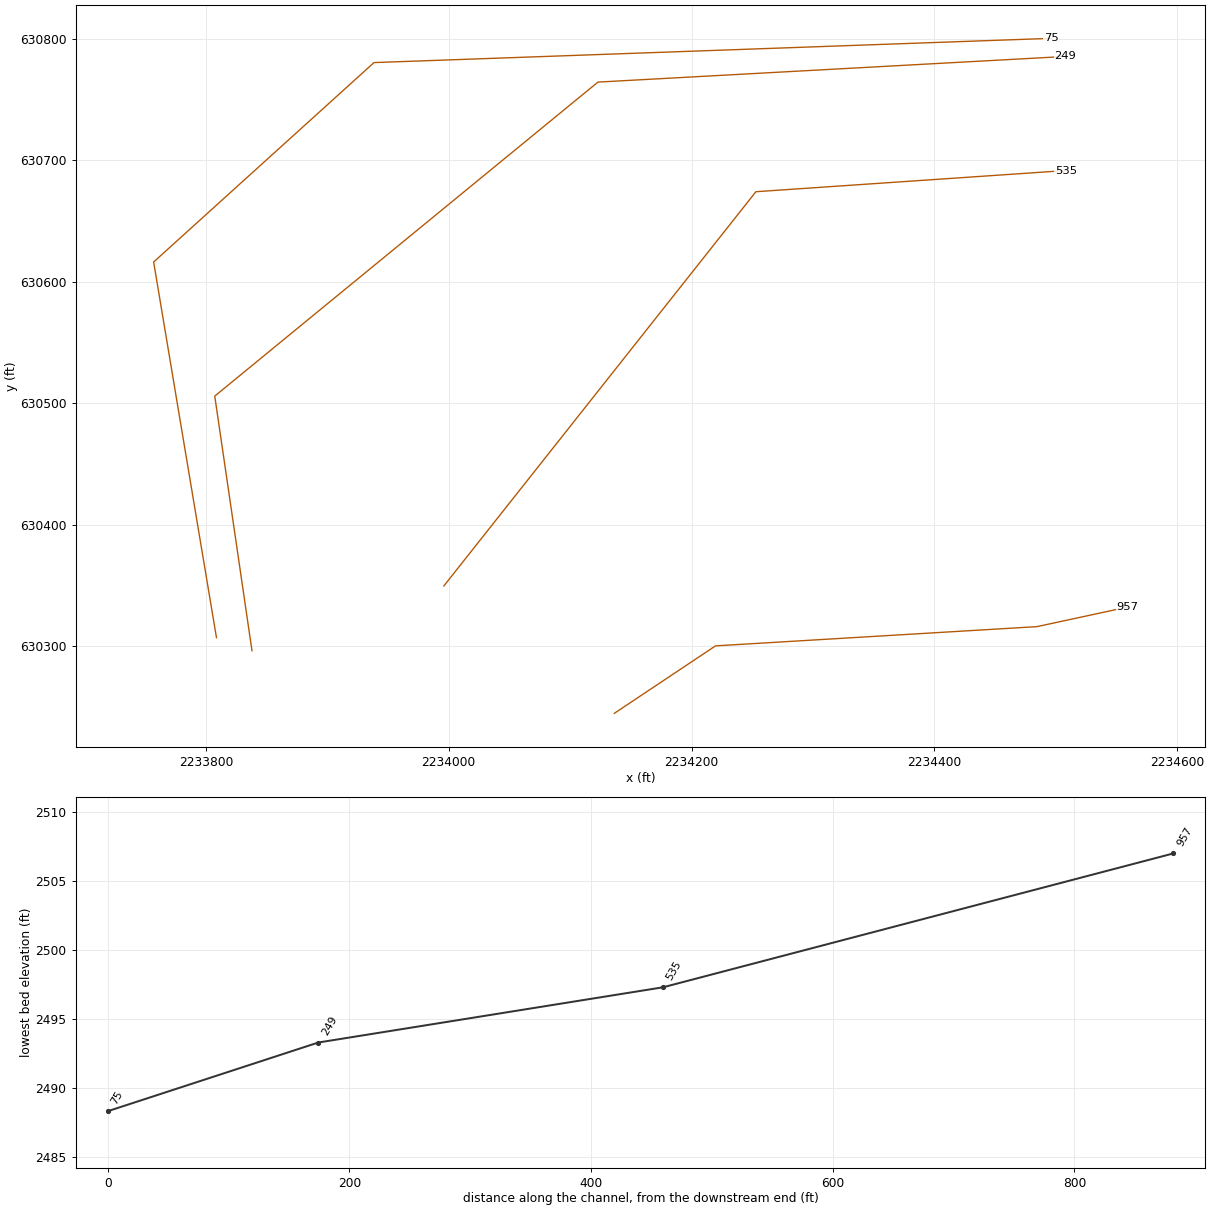
HEC-RAS study ROCKYRN.prj: ROCKYRN

--- ROCKYRN.g01 (geometry) --- (continued)

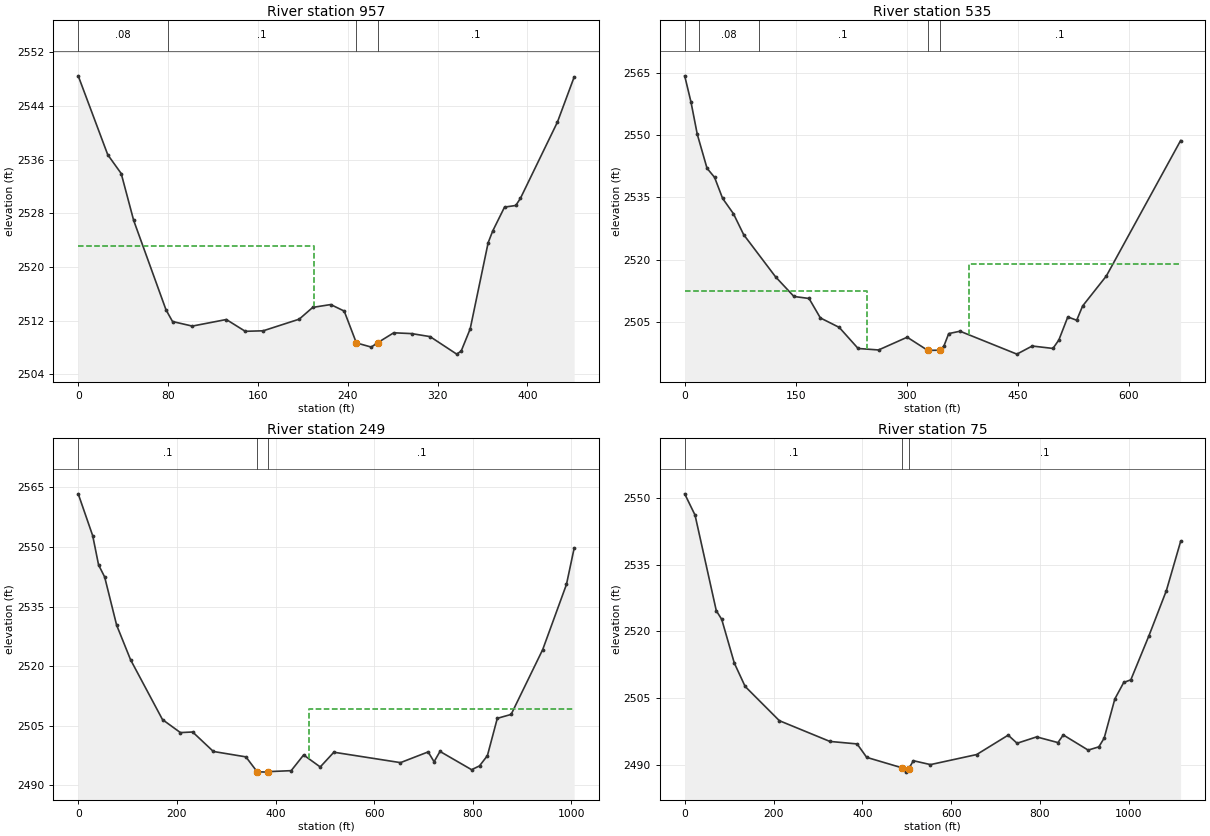
Type RM Length L Ch R = 1 ,957     ,415.6,422.4,430
XS GIS Cut Line= 4
2234136.33770582630244.5354756942234219.73968346 630300.13193748
2234484.47644554630315.9781808942234559.02206012630332.054882794
#Sta/Elev= 30
       0 2548.51    26.3 2536.75    38.3 2533.94    49.4 2526.95    78.2 2513.62
      84 2511.88   101.6  2511.2   131.9 2512.18   148.8 2510.42   164.8  2510.5
   196.8 2512.23   208.9 2513.99   224.9 2514.41   236.9 2513.44  247.732508.695
     261 2508.07  266.562508.708     281  2510.2     297 2510.08   313.4 2509.63
   337.1 2507.02   341.1 2507.48   349.1 2510.78   365.1 2523.63   369.2 2525.39
   379.7 2528.94   389.7 2529.18   393.8 2530.23   426.8 2541.61   441.7 2548.33
#Mann= 4 ,-1,0
       0     .08       0      80      .1       0  247.73    .045       0
  266.56      .1       0
#XS Ineff= 2 , 0
          210.11 2523.19
Permanent Ineff=
       F       F
Bank Sta=247.73,266.56
XS Rating Curve= 0 ,0
Exp/Cntr(USF)=0,0
Exp/Cntr=0.3,0.1

Type RM Length L Ch R = 1 ,535     ,289.6,285.2,278.3
XS GIS Cut Line= 3
2233995.95967927630349.4814371982234252.98500099  630674.2075536
2234508.25251647630691.647529086
#Sta/Elev= 30
       0 2564.27     8.5 2557.99      17 2550.22    30.2 2542.03    40.4 2539.84
    51.2  2534.8    65.9 2531.09    79.7 2526.06   122.8 2515.91   147.6 2511.19
     168 2510.71   183.3 2506.03   208.8 2503.75   234.3 2498.68   261.9 2498.32
   300.6 2501.39328.3889 2498.22344.59882498.263   350.2 2499.26   356.7 2502.26
     372 2502.83   448.8 2497.32   469.5 2499.27   497.5 2498.69   505.5 2500.72
   517.6 2506.27   529.6 2505.47   537.6  2508.9   569.7 2516.13     670  2548.7
#Mann= 5 ,-1,0
       0      .1       0      20     .08       0     100      .1       0
328.3889    .045       0344.5988      .1       0
#XS Ineff= 2 , 0
          246.14 2512.48  383.61         2518.97
Permanent Ineff=
       F       F
Bank Sta=328.3889,344.5988
XS Rating Curve= 0 ,0
Exp/Cntr(USF)=0,0
Exp/Cntr=0.3,0.1

Type RM Length L Ch R = 1 ,249     ,171.9,174.4,169.2
XS GIS Cut Line= 4
2233837.93060324630296.1180502842233807.26515162630505.869739378
2234122.89130428630764.4964625112234507.75776706630785.607026942
#Sta/Elev= 30
       0 2563.36    29.4 2552.81    41.3 2545.46    53.6 2542.44    77.9 2530.31
   106.2 2521.59   170.9 2506.54   207.2 2503.27     232 2503.42     274 2498.52
     340 2497.16   362.8 2493.41   383.8 2493.32385.77972493.443   431.8 2493.69
     457 2497.64   490.7 2494.62   518.3 2498.33   653.4 2495.71   709.5 2498.41
   721.5 2495.93   733.5 2498.53   797.6 2493.93   813.6 2494.89   829.6 2497.46
   849.7 2506.86   877.7 2507.84   941.8 2524.18   989.9 2540.56  1005.5 2549.68
#Mann= 3 ,-1,0
       0      .1       0   362.8    .045       0385.7797      .1       0
#XS Ineff= 2 , 0
                          468.74         2509.31
Permanent Ineff=
       F       F
Bank Sta=362.8,385.7797
XS Rating Curve= 0 ,0
Exp/Cntr(USF)=0,0
Exp/Cntr=0.3,0.1

Type RM Length L Ch R = 1 ,75      ,,,
XS GIS Cut Line= 4
 2233808.6885011630306.9137171092233756.92888345630616.315542969
2233938.43009252630780.5693985062234496.18665322630800.543788062
#Sta/Elev= 30
       0 2550.89    23.3 2546.12    71.2 2524.61    83.4 2522.68   111.8 2512.84
   136.1  2507.6   213.2  2499.9   326.9 2495.24   388.2 2494.68   409.8 2491.66
490.34872489.276   497.9 2488.34504.57662489.111   514.8 2490.91   553.4 2490.03
   657.4 2492.29   728.3 2496.65   748.4 2494.83   792.4 2496.26   840.4 2494.98
   852.4  2496.7   908.4 2493.29   932.5 2494.02   944.5 2495.99   968.5 2504.79
   988.5 2508.49  1004.5 2509.09  1045.4 2519.03  1084.6 2529.16  1116.6 2540.19
#Mann= 3 ,-1,0
       0      .1       0490.3487    .045       0504.5766      .1       0
Bank Sta=490.3487,504.5766
XS Rating Curve= 0 ,0
Exp/Cntr(USF)=0,0
Exp/Cntr=0.3,0.1
LCMann Table=0

Chan Stop Cuts=-1
Use User Specified Reach Order=0
Composite Channel Slope=5